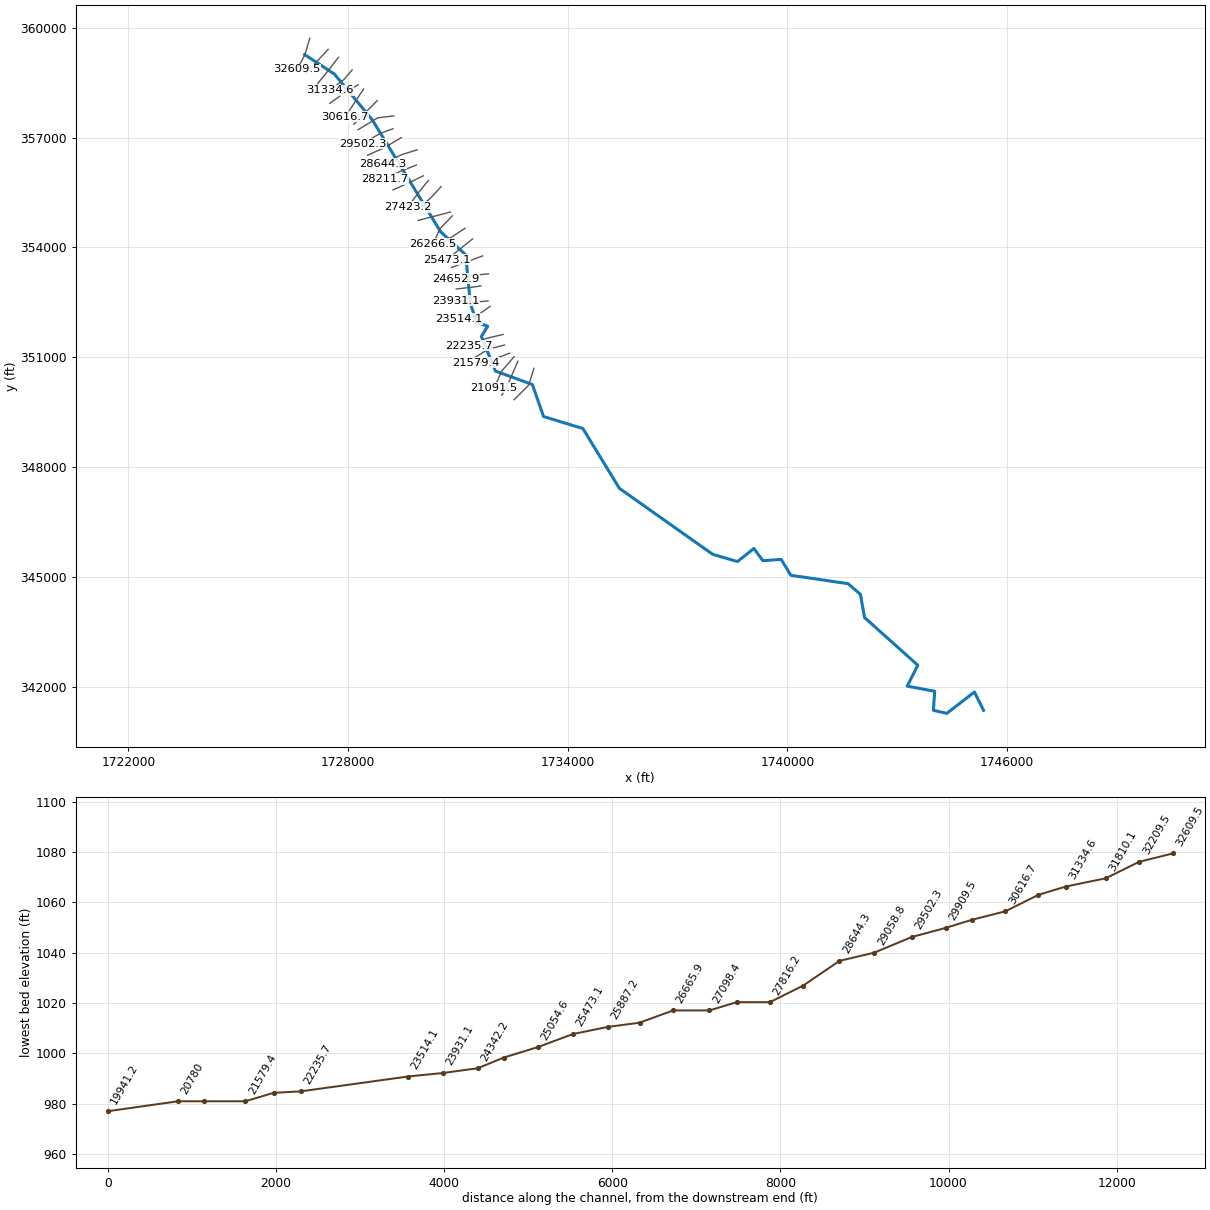
--- LBngmnCrk.prj (project) ---

Proj Title=LBngmnCrk
Current Plan=p01
Default Exp/Contr=0,0
English Units
Geom File=g01
Flow File=f01
Plan File=p01
BEGIN DESCRIPTION:
END DESCRIPTION:
DSS Export Rating Curves= 0
DSS Export Rating Curve Sorted= 0
DSS Export Volume Flow Curves= 0
DXF OffsetX= 0
DXF OffsetY= 0
DXF ScaleX= 0
DXF ScaleY= 0

--- LBngmnCrk.p01 (plan) ---

Plan Title=Floodplain
Program Version=4.00
Geom File=g01
Flow File=f01
K Sum by GR=0
Std Step Tol=0.01
Critical Tol=0.01
Num of Std Step Trials=20
Max Error Tol=0.3
Flow Tol Ratio=0.001
Split Flow NTrial=30
Split Flow Tol=0.02
Split Flow Ratio=0.02
Log Output Level=0
Friction Slope Method=1
Unsteady Friction Slope Method=2
Unsteady Bridges Friction Slope Method=1
Global Log Level=0
CheckData=False
Run HTab=0
Run UNet=0
Run PostProcess=0
UNET Theta=0
UNET Theta Warmup=0
UNET ZTol=0
UNET ZSATol=0
UNET MxIter=0
UNET MaxInSteps=0
UNET DtIC=0
UNET DtMin=0
UNET MaxCRTS=0
UNET WFStab=0
UNET SFStab=0
UNET WFX=0
UNET SFX=0
UNET DSS MLevel=0
UNET DZMax Abort=0
UNET Convert EG Bridges=0
UNET Use Existing IB Tables=0
UNET Froude Limit=0
UNET Froude Power=0
Write IC File=0
Echo Input=False
Echo Output=False
Write Detailed=0

--- LBngmnCrk.f01 (steady flow) ---

Flow Title=NFF Regression Equation
Program Version=4.00
Number of Profiles= 1
Profile Names=P100yr
River Rch & RM=LBngmnCrk,Main            ,32609.5
  747.42
River Rch & RM=LBngmnCrk,Main            ,31810.1
  768.17
River Rch & RM=LBngmnCrk,Main            ,31334.6
965.1096
River Rch & RM=LBngmnCrk,Main            ,29502.3
1010.117
River Rch & RM=LBngmnCrk,Main            ,27423.2
 1121.86
River Rch & RM=LBngmnCrk,Main            ,27098.4
  1299.6
River Rch & RM=LBngmnCrk,Main            ,25473.1
1322.422
River Rch & RM=LBngmnCrk,Main            ,25054.6
1469.992
River Rch & RM=LBngmnCrk,Main            ,23931.1
 1552.82
River Rch & RM=LBngmnCrk,Main            ,23514.1
1801.185
River Rch & RM=LBngmnCrk,Main            ,17114.1
1944.272
River Rch & RM=LBngmnCrk,Main            ,15114.1
2222.824
River Rch & RM=LBngmnCrk,Main            ,7574.6
2457.074
River Rch & RM=LBngmnCrk,Main            ,1914.1
2729.139
River Rch & RM=LBngmnCrk,Main            ,1451.2
6086.096
River Rch & RM=LBngmnCrk,Main            ,265.6
6986.264
Boundary for River Rch & Prof#=LBngmnCrk,Main            , 1
Up Type= 0
Dn Type= 3
Dn Slope=0.00525
DSS Import GetInterval= 0
DSS Import GetPeak= 0
DSS Import FillOption= 0

--- LBngmnCrk.g01 (geometry) ---

Geom Title=USGS 3m DEM
Program Version=4.00

River Reach=LBngmnCrk       ,Main
Reach XY= 30
     1726814.178      359263.616     1727630.239      358730.048
     1728662.621      357482.259     1730529.951      354427.901
     1731216.035      353795.292     1731339.019      352481.973
     1731510.562      351958.307     1731814.774      351848.302
     1731643.842      351567.609     1732026.203       350624.91
     1733035.537      350257.087     1733341.304      349382.655
     1734415.504       349055.38     1735411.193      347423.924
     1737960.468      345621.719     1738636.672      345424.155
     1739086.667      345780.162     1739331.507      345448.339
     1739832.229       345482.35     1740095.918      345049.979
     1741659.468      344819.793     1741995.901      344528.821
     1742109.564      343896.187     1743563.508      342593.576
     1743274.453      342023.445       1744024.5      341882.891
     1743989.496      341362.408     1744358.727      341281.107
     1745109.668      341862.933     1745358.762      341364.027

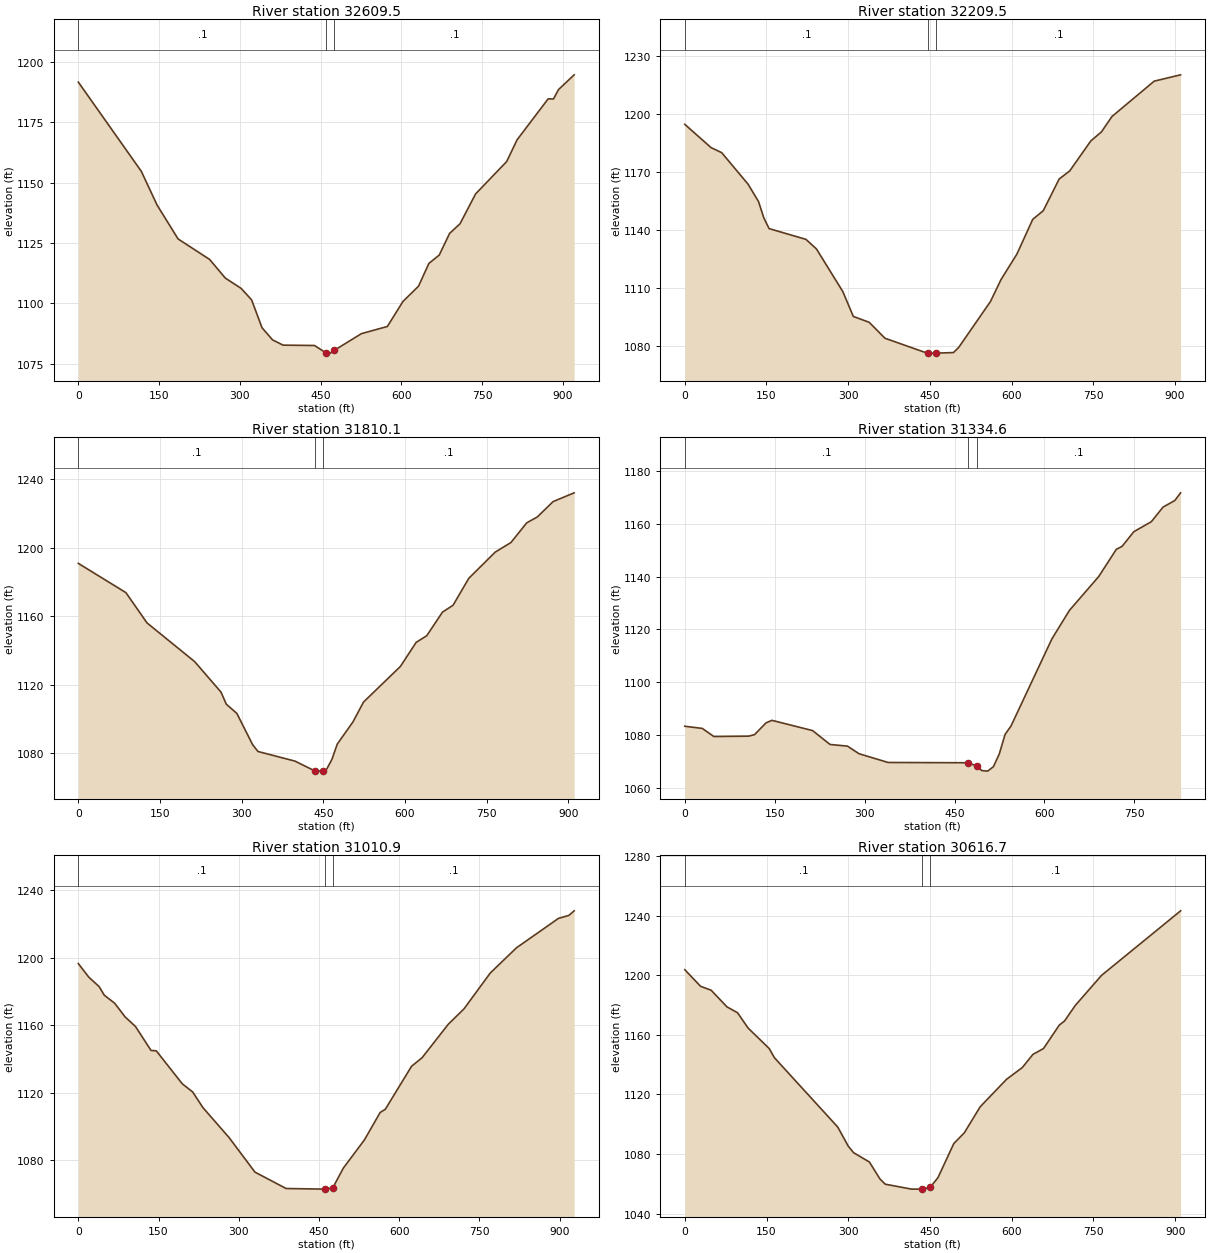
Type RM Length L Ch R = 1 ,32609.5 ,410.581,400,394.436
XS GIS Cut Line= 3
     1726954.795      359707.727     1726822.957      359258.828
     1726606.165      358861.378
#Sta/Elev= 30
       0 1191.69     117 1154.72   146.2 1140.78   185.2 1126.73   243.7 1118.25
   272.9 1110.52   302.2 1106.26   321.7 1101.51   341.1 1089.94   360.6 1084.92
   380.1 1082.74   438.6 1082.59   460.4 1079.44   467.9 1079.43   475.4 1080.61
   525.7 1087.51   573.8 1090.47   602.7 1100.82   631.6 1107.15   650.9 1116.59
   670.1 1120.05   689.4 1129.05   708.7 1133.03   737.6 1145.38   795.4 1158.81
   814.6 1167.78   872.4 1184.79   882.1 1184.69   891.7 1188.62   920.6 1194.71
#Mann= 3 , 0 , 0
       0      .1       0   460.4    .045       0   475.4      .1       0
Bank Sta=460.4,475.4
XS Rating Curve= 0 ,0
Exp/Cntr=0.3,0.1

Type RM Length L Ch R = 1 ,32209.5 ,397.224,399.465,401.173
XS GIS Cut Line= 3
      1727457.82       359405.13     1727147.026      359073.298
     1726839.367      358736.967
#Sta/Elev= 30
       0 1194.79    48.4 1182.68    67.7 1180.11   116.1 1163.79   135.4 1154.73
   145.1 1146.28   154.8  1140.7   222.5 1135.12   241.8 1130.14   290.2 1108.03
   309.5 1095.14   338.6  1092.1   367.6 1083.83     445 1076.11   447.1 1076.11
   462.1 1076.11   493.4  1076.4   503.1 1079.12   561.3 1102.87   580.7 1114.28
   609.8 1127.45   638.9 1145.48   658.3 1150.01   687.4 1166.41   706.8 1170.61
   745.6 1186.18     765 1190.84   784.4 1198.85     862 1217.19   910.5 1220.47
#Mann= 3 , 0 , 0
       0      .1       0   447.1    .045       0   462.1      .1       0
Bank Sta=447.1,462.1
XS Rating Curve= 0 ,0
Exp/Cntr=0.3,0.1

Type RM Length L Ch R = 1 ,31810.1 ,479.241,475.499,472.024
XS GIS Cut Line= 3
     1727738.412      359190.357     1727460.382      358828.615
     1727172.045      358477.275
#Sta/Elev= 30
       0 1190.94    87.4 1173.85   126.2 1156.15   213.6 1133.57   262.1 1115.72
   271.8 1108.66   291.2 1103.28   320.3 1084.94     330 1081.03     398  1075.4
   434.5 1069.66   436.8 1069.55   449.5  1069.9   456.2 1070.68   465.9 1076.46
   475.6 1085.33   504.6 1098.37   523.9 1109.91   591.6 1130.71   620.6 1144.79
     640 1148.66     669 1162.48   688.3 1166.45   717.3 1182.22   765.7  1197.5
   794.7 1203.13   823.7 1214.63   843.1 1218.05   872.1 1227.03   910.8 1232.16
#Mann= 3 , 0 , 0
       0      .1       0   434.5    .045       0   449.5      .1       0
Bank Sta=434.5,449.5
XS Rating Curve= 0 ,0
Exp/Cntr=0.3,0.1

Type RM Length L Ch R = 1 ,31334.6 ,329.184,323.708,319.672
XS GIS Cut Line= 3
     1728112.572      358845.904     1727892.565      358587.787
      1727505.13      358291.157
#Sta/Elev= 30
       0 1083.28    29.1 1082.47    48.5 1079.39   106.6 1079.53   116.3 1080.11
   135.7  1084.6   145.4 1085.52   213.2 1081.64   242.3 1076.38   271.3 1075.75
   290.7 1072.86   339.2 1069.55     472 1069.44     487 1068.25   495.3 1066.48
   505.1 1066.27   514.8 1067.95   524.6 1072.78   534.3 1080.21   544.1 1083.35
   612.4 1116.42   641.7 1127.24   690.5 1140.06   719.8 1150.35   729.5  1151.5
     749 1157.04   778.3 1160.86   797.8 1166.38   817.3 1168.86   827.1 1171.79
#Mann= 3 , 0 , 0
       0      .1       0     472    .045       0     487      .1       0
Bank Sta=472,487
XS Rating Curve= 0 ,0
Exp/Cntr=0.3,0.1

Type RM Length L Ch R = 1 ,31010.9 ,383.967,394.195,402.984
XS GIS Cut Line= 3
     1728277.455      358440.761     1727868.006      358197.673
     1727503.055       357932.25
#Sta/Elev= 30
       0 1196.54    19.4 1188.55    38.9 1182.89    48.6  1177.8      68 1173.04
    87.5 1164.95   106.9 1159.29     136 1145.09   145.8 1144.87   194.4 1125.35
   213.8 1120.53   233.2 1111.19   281.8 1093.58   330.4 1073.04   388.7 1063.34
   460.9 1062.98   475.9 1063.72   495.8  1075.5     535 1092.08   564.5 1108.34
   574.3 1110.31   623.3 1135.74   642.9 1140.76     692 1160.62   721.4 1169.73
   770.5 1190.94   819.5 1205.87     898 1223.27   917.6 1225.07   927.4 1227.76
#Mann= 3 , 0 , 0
       0      .1       0   460.9    .045       0   475.9      .1       0
Bank Sta=460.9,475.9
XS Rating Curve= 0 ,0
Exp/Cntr=0.3,0.1

Type RM Length L Ch R = 1 ,30616.7 ,405.913,401.401,396.89
XS GIS Cut Line= 3
     1728425.415      358323.496     1728174.122      357944.185
     1727922.828      357564.874
#Sta/Elev= 30
       0 1203.73      29 1192.57    48.4 1189.94    77.4 1178.77    96.8 1174.83
   116.2 1164.55   154.9 1150.82   164.6 1144.59   280.7 1098.11   300.1 1085.21
   309.8 1080.89   338.8 1074.63   358.2 1063.25   367.9 1059.74   416.3 1056.43
   435.3 1056.43   450.3 1057.56   464.7 1064.18   493.7 1087.03   513.1 1094.28
   542.1 1111.69   590.5 1130.15   619.6  1138.1   638.9 1146.88   658.3 1150.78
   687.3 1166.53     697 1169.32   716.4 1179.62   764.8  1199.9     910 1243.25
#Mann= 3 , 0 , 0
       0      .1       0   435.3    .045       0   450.3      .1       0
Bank Sta=435.3,450.3
XS Rating Curve= 0 ,0
Exp/Cntr=0.3,0.1

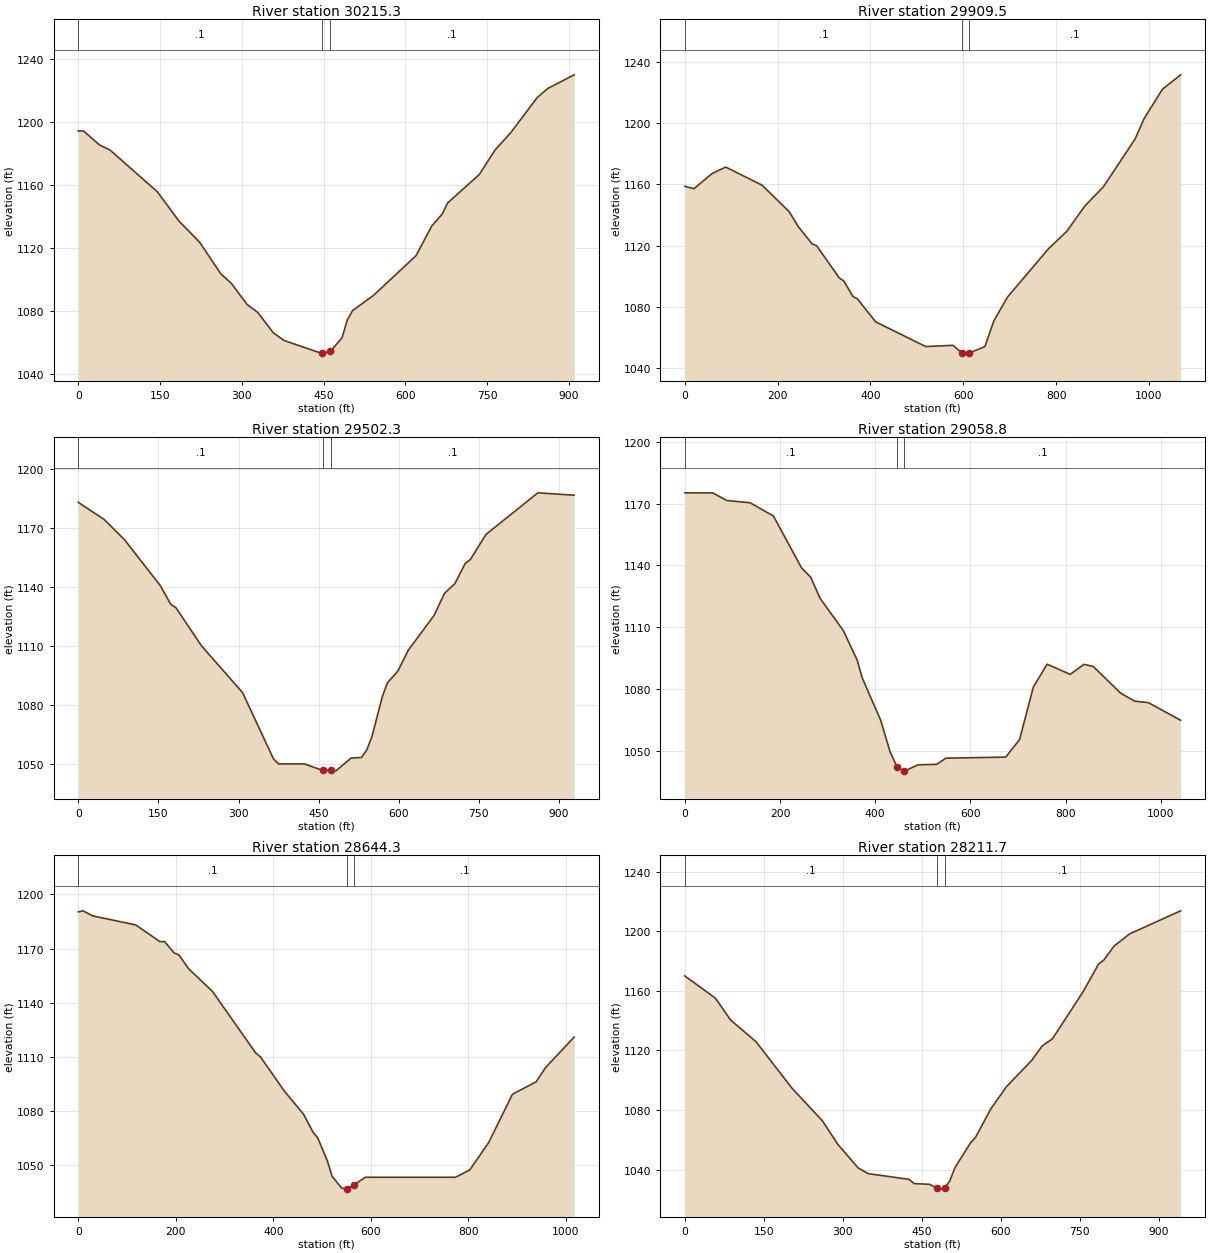
Type RM Length L Ch R = 1 ,30215.3 ,311.248,305.751,300.253
XS GIS Cut Line= 3
     1728798.956       358006.52     1728477.223      357684.786
     1728155.489      357363.053
#Sta/Elev= 30
       0  1194.5     9.7 1194.41    38.7 1185.62    58.1 1182.33   145.2 1155.69
   183.9 1137.45   222.7 1123.58   261.4 1103.59   280.7  1097.5   309.8 1083.97
   329.1 1078.99   358.2 1065.87   377.6 1061.07   445.3 1053.03   447.5 1053.04
   462.5 1054.12     484 1062.79   493.7  1074.2   503.4 1080.11   542.1  1089.9
   619.6    1115   648.6 1133.91     668 1141.64   677.7 1148.64   735.7 1166.66
   764.8 1182.33   793.8 1193.45   842.2 1215.73   861.6 1221.54     910  1230.2
#Mann= 3 , 0 , 0
       0      .1       0   447.5    .045       0   462.5      .1       0
Bank Sta=447.5,462.5
XS Rating Curve= 0 ,0
Exp/Cntr=0.3,0.1

Type RM Length L Ch R = 1 ,29909.5 ,407.735,407.185,406.634
XS GIS Cut Line= 3
     1729249.381      357591.481     1728812.227      357537.511
     1728274.292      357214.263
#Sta/Elev= 30
       0 1158.75    19.6  1157.1    58.7 1167.03    88.1 1171.26   166.4 1159.45
   225.1 1142.06   244.7 1132.27   274.1 1121.21   283.9 1119.94   332.8 1098.94
   342.6 1096.94   362.2 1086.83     372 1085.23   411.1 1070.28   518.9 1054.16
   577.8 1054.95   597.2 1049.91   607.2 1049.87   612.2 1049.87   646.4 1054.16
     666 1071.07   695.4 1086.52   783.7 1118.03   822.9 1129.32   862.1 1145.99
   901.4 1158.23     970 1189.53   989.6 1202.93  1028.8 1221.99  1068.1 1231.42
#Mann= 3 , 0 , 0
       0      .1       0   597.2    .045       0   612.2      .1       0
Bank Sta=597.2,612.2
XS Rating Curve= 0 ,0
Exp/Cntr=0.3,0.1

Type RM Length L Ch R = 1 ,29502.3 ,442.624,443.493,444.118
XS GIS Cut Line= 3
      1729228.78      357240.647      1728876.99       357111.15
      1728396.66      356835.904
#Sta/Elev= 30
       0 1182.82    48.1 1174.19    86.5 1163.83   153.8 1140.41     173 1131.02
   182.6 1129.32   230.7 1109.88   307.6 1086.09   365.3  1052.5   374.9 1049.87
   423.4 1049.87   457.3 1046.59   472.3 1046.56   481.7  1046.2   510.8 1052.84
   530.3 1053.15     540 1056.91   549.7  1063.6   569.1  1083.9   578.8  1091.1
   598.3 1097.01   617.7 1107.58   666.2 1125.35   685.7 1136.59   705.1 1141.51
   724.5 1151.75   734.2 1153.79   763.4 1166.52   860.5 1187.67   928.5 1186.46
#Mann= 3 , 0 , 0
       0      .1       0   457.3    .045       0   472.3      .1       0
Bank Sta=457.3,472.3
XS Rating Curve= 0 ,0
Exp/Cntr=0.3,0.1

Type RM Length L Ch R = 1 ,29058.8 ,416.43,414.582,412.745
XS GIS Cut Line= 3
     1729456.437      356997.113     1728992.317      356723.254
     1728534.255       356516.42
#Sta/Elev= 30
       0 1175.27    58.8 1175.23    88.2 1171.54   137.2 1170.44   186.2    1164
     245 1138.88   264.5 1134.23   284.1 1124.03   333.1 1108.31   362.5 1093.72
   372.3 1085.54   411.5 1064.73   431.1 1049.49   446.2 1041.84   460.5 1040.02
   461.2 1040.02   489.9 1043.09   529.1 1043.31   548.6 1046.33   674.2 1046.84
   703.2 1055.33   732.2 1080.94   761.2    1092   809.5 1087.02   838.5 1091.91
   857.8 1090.92   915.8 1077.85   944.8 1074.04   973.8  1073.3  1041.5 1064.73
#Mann= 3 , 0 , 0
       0      .1       0   446.2    .045       0   461.2      .1       0
Bank Sta=446.2,461.2
XS Rating Curve= 0 ,0
Exp/Cntr=0.3,0.1

Type RM Length L Ch R = 1 ,28644.3 ,434.79,432.556,431.742
XS GIS Cut Line= 3
     1729886.224      356663.201     1729454.467      356528.277
     1728947.151      356280.016
#Sta/Elev= 30
       0 1190.32     9.8 1190.89    29.5 1188.08     118 1183.06   167.2 1173.85
     177 1173.87   196.7 1167.53   206.5 1166.46   226.2 1158.84   275.3 1146.23
   363.8 1112.19   373.7 1109.96   422.8    1091   462.1 1078.21   481.6 1068.23
   491.3 1065.04   510.8 1052.43   520.5  1043.9     540 1037.38   549.7 1036.74
   551.4 1036.91   566.4 1039.15   588.7 1043.31   773.7 1043.31   802.9 1047.33
   841.9 1062.53   890.6  1089.3   939.2 1096.18   958.7 1104.11  1017.2 1120.93
#Mann= 3 , 0 , 0
       0      .1       0   551.4    .045       0   566.4      .1       0
Bank Sta=551.4,566.4
XS Rating Curve= 0 ,0
Exp/Cntr=0.3,0.1

Type RM Length L Ch R = 1 ,28211.7 ,393.689,395.523,395.118
XS GIS Cut Line= 3
     1729866.673      356248.105     1729407.059      356067.606
     1729006.216      355867.186
#Sta/Elev= 30
       0 1170.08    58.1 1155.16    87.1 1140.44   135.5 1125.83   203.3 1094.81
   261.4 1072.77   290.5 1057.11   329.2 1041.17   348.6 1037.29     426 1033.46
   435.7 1030.62   464.7 1030.15   479.4 1027.53   484.1  1026.9   494.4 1027.86
   503.5 1032.52   513.3 1041.37   542.5 1057.85   552.2 1061.62   581.5 1080.86
   610.7 1095.54   659.4  1113.5   678.9 1123.07   698.4 1127.85   756.8 1159.54
   786.1 1178.07   795.8 1180.68   815.3 1190.02   844.5 1198.21   941.9  1213.8
#Mann= 3 , 0 , 0
       0      .1       0   479.4    .045       0   494.4      .1       0
Bank Sta=479.4,494.4
XS Rating Curve= 0 ,0
Exp/Cntr=0.3,0.1

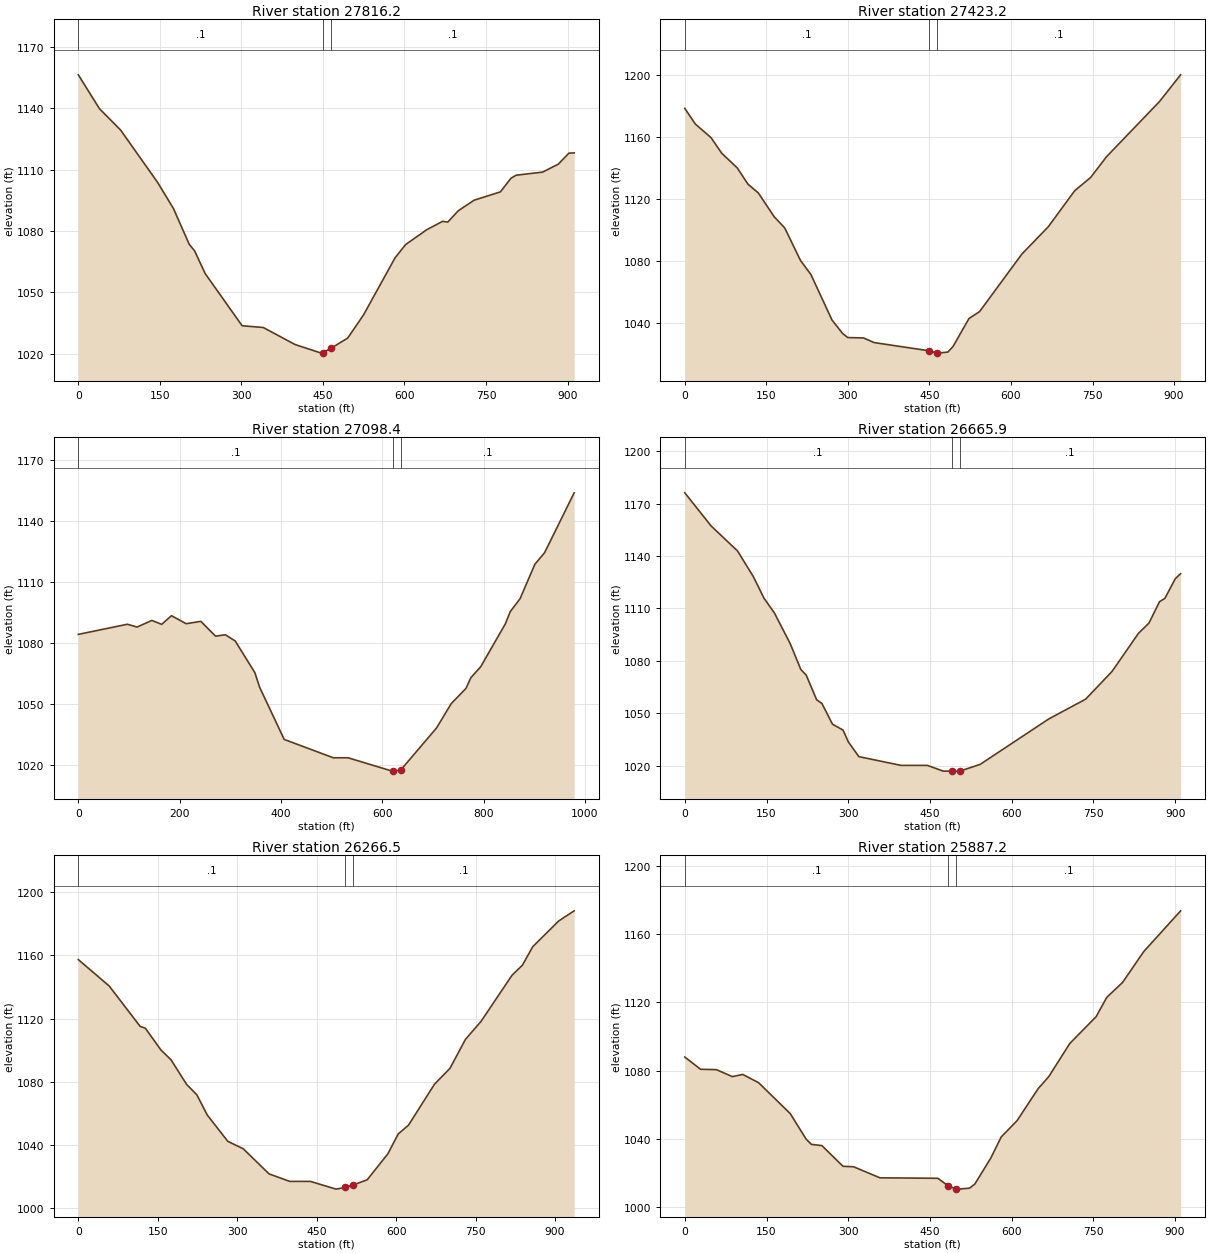
Type RM Length L Ch R = 1 ,27816.2 ,382.925,392.952,405.124
XS GIS Cut Line= 3
     1730054.498      355954.585     1729643.903      355754.416
     1729227.783      355569.706
#Sta/Elev= 30
       0  1156.3    38.9 1139.74    77.8 1129.32   145.8 1103.77   174.9 1091.01
   204.1 1073.47   213.8 1070.35   233.3 1059.23   301.3 1033.72   340.2 1032.86
   398.5 1024.56   447.1 1020.34   449.3 1020.51   464.3 1022.63   495.5 1027.69
   524.6 1038.99   582.7 1066.92   602.1 1073.39   640.8  1080.6   669.9 1084.71
   679.6 1084.36     699 1089.91     728 1095.04   776.4 1099.12   795.8 1105.75
   805.5 1107.27   853.9 1108.76     883 1112.66   902.4 1118.04   912.1 1118.18
#Mann= 3 , 0 , 0
       0      .1       0   449.3    .045       0   464.3      .1       0
Bank Sta=449.3,464.3
XS Rating Curve= 0 ,0
Exp/Cntr=0.3,0.1

Type RM Length L Ch R = 1 ,27423.2 ,328.974,324.855,319.4
XS GIS Cut Line= 3
     1730194.719      355825.808     1729906.558      355474.234
     1729638.613      355103.546
#Sta/Elev= 30
       0 1178.19    19.3 1168.12    48.4 1159.26    67.7 1149.34    96.7 1139.71
   116.1 1129.34   135.4 1123.58   164.4 1108.31   183.8 1101.09   212.8 1080.12
   232.1 1070.96   270.8 1041.65   290.2 1033.05   299.8 1030.38   328.8 1030.14
   348.2 1027.15   449.7 1021.83   464.3 1020.34   464.7 1020.34   483.8 1021.02
   493.5 1024.66   522.7 1042.66   542.2 1047.12     620 1084.21   668.7 1101.89
   717.3 1125.13   746.5 1133.62   775.7    1147     873 1182.54     912 1199.82
#Mann= 3 , 0 , 0
       0      .1       0   449.7    .045       0   464.7      .1       0
Bank Sta=449.7,464.7
XS Rating Curve= 0 ,0
Exp/Cntr=0.3,0.1

Type RM Length L Ch R = 1 ,27098.4 ,442.901,432.496,422.09
XS GIS Cut Line= 3
     1730544.655      355659.364     1730247.822      355340.943
     1729837.652      354984.742
#Sta/Elev= 30
       0 1084.25    96.7 1089.23   116.1 1087.86   145.1 1091.12   164.5 1089.19
   183.8 1093.44   212.8  1089.5   241.8 1090.65   270.9 1083.38   290.2 1084.07
   309.6 1081.02   348.3 1065.52   357.9 1058.25   406.3 1032.64   503.2 1023.62
   532.3 1023.62   619.6 1017.06   621.3 1017.06   636.3 1017.61   706.9 1038.24
     736 1050.23   765.1 1057.72   774.8 1062.99   794.3  1068.4   842.8 1089.44
   852.5 1095.46   871.9  1101.8     901 1118.68   920.4 1124.46   978.6 1153.81
#Mann= 3 , 0 , 0
       0      .1       0   621.3    .045       0   636.3      .1       0
Bank Sta=621.3,636.3
XS Rating Curve= 0 ,0
Exp/Cntr=0.3,0.1

Type RM Length L Ch R = 1 ,26665.9 ,377.691,399.394,422.649
XS GIS Cut Line= 3
     1730796.315      354965.537     1730356.049      354850.685
     1729915.783      354735.833
#Sta/Elev= 30
       0  1176.1    48.4 1157.14    96.8 1142.88   125.9 1128.18   145.2 1115.95
   164.6 1107.38   193.6 1089.83     213  1075.1   222.7 1072.02     242 1057.82
   251.7  1055.7   271.1 1043.86   290.4 1040.55   300.1 1033.79   319.5 1025.34
   396.9 1020.34   445.3 1020.33   474.4 1017.06   489.8 1017.06   504.8 1017.06
   542.1 1020.91     668 1046.88   735.7 1058.19   784.1 1074.03   832.6 1095.79
   851.9 1101.67   871.3 1113.91     881 1115.74   900.3 1127.04     910 1129.87
#Mann= 3 , 0 , 0
       0      .1       0   489.8    .045       0   504.8      .1       0
Bank Sta=489.8,504.8
XS Rating Curve= 0 ,0
Exp/Cntr=0.3,0.1

Type RM Length L Ch R = 1 ,26266.5 ,392.887,379.249,364.06
XS GIS Cut Line= 3
      1730848.39      354862.795     1730512.659      354510.324
     1730325.418      354101.797
#Sta/Elev= 30
       0 1157.39    58.4 1140.63   116.8 1115.11   126.6 1113.95   155.8 1100.28
   175.2 1093.91   204.4 1078.45   223.9  1071.8   243.4 1059.08   282.3 1042.38
   311.5 1037.68   360.2 1021.79   399.2 1017.06   438.1 1017.06   486.8 1012.17
   504.4 1013.32   519.4 1014.85   545.4 1018.08   584.5 1034.53     604 1047.08
   623.5 1052.66   672.4 1078.51   701.7 1088.57     731 1106.95   760.3 1118.26
   818.9 1147.49   838.5 1153.85     858 1165.54   906.9 1181.79   936.2 1188.24
#Mann= 3 , 0 , 0
       0      .1       0   504.4    .045       0   519.4      .1       0
Bank Sta=504.4,519.4
XS Rating Curve= 0 ,0
Exp/Cntr=0.3,0.1

Type RM Length L Ch R = 1 ,25887.2 ,412.769,414.098,415.426
XS GIS Cut Line= 3
     1731196.769      354523.146     1730816.222      354273.822
     1730443.612      354012.198
#Sta/Elev= 30
       0  1087.9      29 1080.73    58.1 1080.51    87.1 1076.44   106.5 1077.69
   135.5 1072.86   193.6 1054.75   222.6 1039.86   232.3 1036.74   251.7 1036.01
   290.4 1023.87   309.8 1023.62   358.2 1017.13   464.6 1016.85   483.2 1012.45
   498.2 1010.62   503.4  1010.5   522.8  1011.1   532.4 1013.45   561.5 1028.57
   580.9 1041.08   609.9  1050.6   648.7 1069.39   668.1  1076.4   706.8 1095.86
   755.2  1111.6   774.6 1122.87   803.7 1131.63   842.4 1149.66   910.2 1173.58
#Mann= 3 , 0 , 0
       0      .1       0   483.2    .045       0   498.2      .1       0
Bank Sta=483.2,498.2
XS Rating Curve= 0 ,0
Exp/Cntr=0.3,0.1

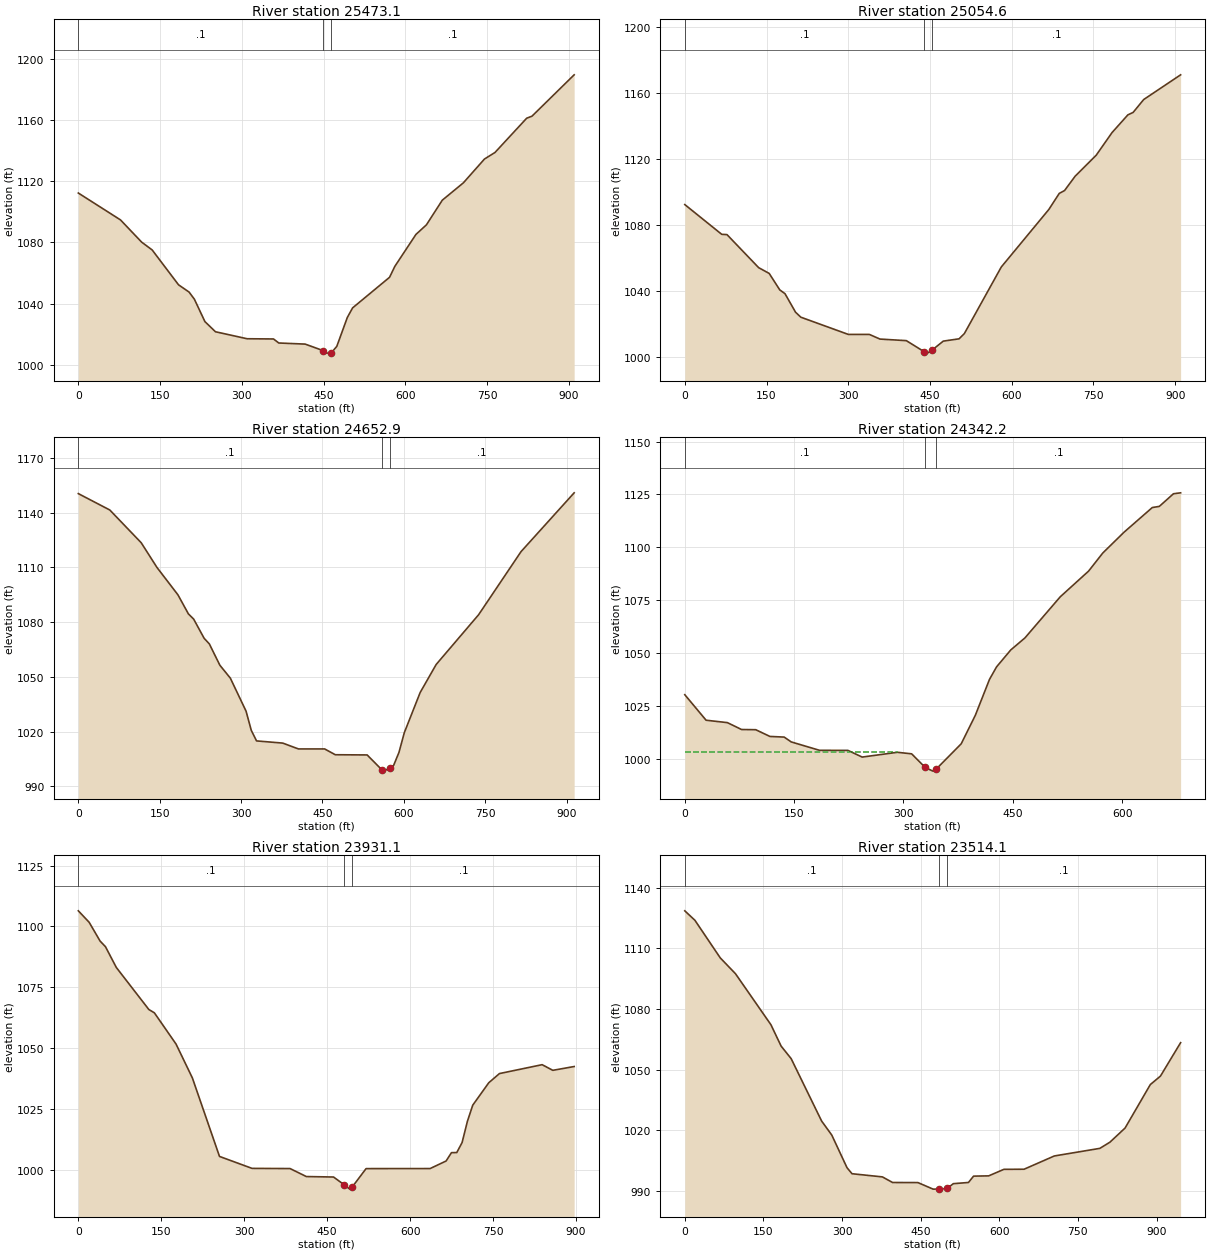
Type RM Length L Ch R = 1 ,25473.1 ,425.536,418.513,411.491
XS GIS Cut Line= 3
     1731402.095      354231.716       1731046.8       353947.48
     1730691.505      353663.244
#Sta/Elev= 30
       0 1112.32    77.4 1094.75   116.2 1080.23   135.5 1075.12   183.9 1052.33
   203.3 1047.56     213 1042.92   232.3 1028.28   251.7 1021.63   309.8 1017.06
   358.2 1016.92   367.9 1014.28   416.3 1013.56   449.1 1009.33     455 1007.66
   464.1 1007.75   474.4 1012.11   493.7 1030.98   503.4 1037.24   571.2 1057.24
   580.9 1064.39   619.6 1085.25   638.9 1091.54     668 1107.65   706.7    1119
   745.4 1134.55   764.8 1138.87   822.9 1161.25   832.6 1162.56     910  1189.6
#Mann= 3 , 0 , 0
       0      .1       0   449.1    .045       0   464.1      .1       0
Bank Sta=449.1,464.1
XS Rating Curve= 0 ,0
Exp/Cntr=0.3,0.1

Type RM Length L Ch R = 1 ,25054.6 ,405.619,401.711,397.804
XS GIS Cut Line= 3
     1731678.357      353768.449     1731251.921      353609.774
     1730825.485        353451.1
#Sta/Elev= 30
       0  1092.4    67.8 1074.39    77.4 1074.23   135.5 1054.23   154.9 1050.72
   174.3 1040.75   183.9 1038.46   203.3 1027.22     213 1024.21   300.1 1013.79
   338.8 1013.78   358.2 1010.97   406.6 1010.02     439 1003.38   445.3 1002.46
     454 1004.32   474.4 1009.73   503.4 1011.12   513.1  1014.3   580.9 1054.63
     668 1089.39   687.3 1099.18     697  1100.9   716.4 1109.58   755.1 1122.32
   784.1 1135.99   813.2 1146.72   822.9 1148.23   842.2    1156     910 1170.97
#Mann= 3 , 0 , 0
       0      .1       0     439    .045       0     454      .1       0
Bank Sta=439,454
XS Rating Curve= 0 ,0
Exp/Cntr=0.3,0.1

Type RM Length L Ch R = 1 ,24652.9 ,312.672,310.707,308.742
XS GIS Cut Line= 3
     1731840.794      353278.855     1731388.883      353234.345
     1730937.878      353144.382
#Sta/Elev= 30
       0 1150.43      58 1141.45   115.9 1123.51   144.9 1109.99   183.6 1094.97
   202.9 1084.52   212.6 1081.66   231.9 1071.14   241.5 1068.07   260.9 1056.38
   280.2 1049.31   309.2  1031.2   318.8  1020.7   328.5  1014.9   376.8  1013.7
   405.8  1010.5   454.1  1010.5   473.7 1007.32   532.4 1007.21   559.9  998.96
   561.7  998.34   574.9 1000.02   581.3 1001.54   591.1 1008.64   600.9  1019.4
   630.2 1041.46   659.6 1056.77   737.9 1084.06   816.1 1118.64     914 1150.86
#Mann= 3 , 0 , 0
       0      .1       0   559.9    .045       0   574.9      .1       0
Bank Sta=559.9,574.9
XS Rating Curve= 0 ,0
Exp/Cntr=0.3,0.1

Type RM Length L Ch R = 1 ,24342.2 ,411.523,411.16,410.796
XS GIS Cut Line= 3
     1731630.711      352948.786     1731399.663      352914.482
     1730955.726      352866.052
#Sta/Elev= 30
       0 1030.25    29.2 1018.18    58.4 1017.04    77.9 1013.78    97.3 1013.69
   116.8  1010.5   136.3  1010.2     146 1007.91   184.9 1003.93   223.8  1003.9
   243.3 1000.74   291.8    1003   311.2 1002.27   329.8  995.83   340.4  994.09
   344.8  995.02   379.2 1007.02   398.6 1020.53     418  1037.5   427.7 1043.43
   447.2 1051.44   466.6 1057.12   515.1 1076.59   553.9 1088.72   573.4 1097.29
   602.5 1107.12   641.3 1118.81     651 1119.37   670.4 1125.34   680.2 1125.78
#Mann= 3 , 0 , 0
       0      .1       0   329.8    .045       0   344.8      .1       0
#XS Ineff= 2 , 0
          291.98 1003.16
Permanent Ineff=
       F       F
Bank Sta=329.8,344.8
XS Rating Curve= 0 ,0
Exp/Cntr=0.3,0.1

Type RM Length L Ch R = 1 ,23931.1 ,404.545,416.912,417.626
XS GIS Cut Line= 3
     1731823.738      352539.913     1731305.628      352491.341
     1730933.237       352545.31
#Sta/Elev= 30
       0 1106.42    19.6 1101.71    39.3 1094.03    49.1  1091.7    68.7 1083.18
   127.6  1065.9   137.5 1064.57   176.7 1051.75   206.2 1037.87   255.3 1005.63
   314.2 1000.72   382.9 1000.65   412.4  997.37   461.5  997.18   480.7  994.02
   490.9  992.21   495.7   993.2   520.4 1000.63   636.2 1000.65   665.1 1003.75
   674.8 1007.18   684.4 1007.22     694 1011.31   703.7 1020.08   713.3 1026.66
   742.3 1035.87   761.6 1039.63   838.8 1043.28   858.1 1040.96   896.7 1042.52
#Mann= 3 , 0 , 0
       0      .1       0   480.7    .045       0   495.7      .1       0
Bank Sta=480.7,495.7
XS Rating Curve= 0 ,0
Exp/Cntr=0.3,0.1

Type RM Length L Ch R = 1 ,23514.1 ,1294.484,1278.392,1276.974
XS GIS Cut Line= 3
      1731877.52      352388.719     1731476.229      352102.237
     1731026.789      352046.631
#Sta/Elev= 30
       0 1128.51    19.3 1123.83    67.7 1105.21    96.7 1097.39   164.4 1072.12
   183.7  1061.6     203 1055.33     261 1024.51   280.4 1017.56   309.4 1001.44
     319  998.43     377  996.86   396.4  994.09   444.7  994.05   473.7  990.81
   485.6  990.82   500.6  991.15   512.3  993.51   541.2   994.1   550.9  997.24
   579.8  997.37   608.7  1000.6   647.2 1000.65     705 1007.22   791.8 1010.98
     811 1014.03   839.9 1021.02   888.1 1042.55   907.4 1046.73   945.9 1063.28
#Mann= 3 , 0 , 0
       0      .1       0   485.6    .045       0   500.6      .1       0
Bank Sta=485.6,500.6
XS Rating Curve= 0 ,0
Exp/Cntr=0.3,0.1

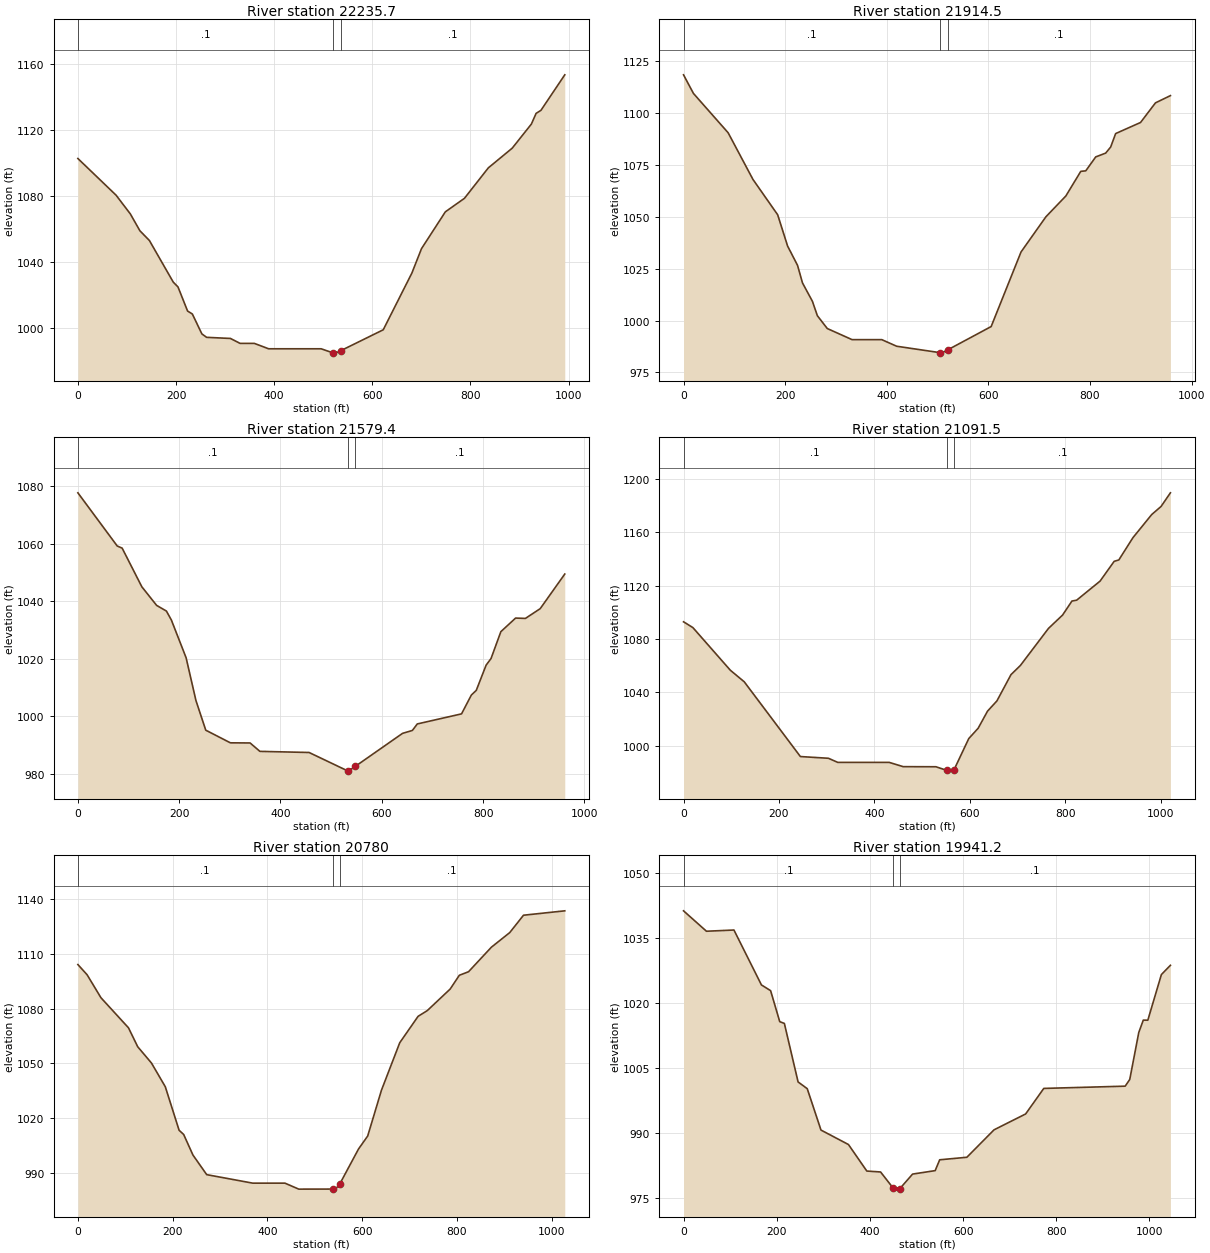
Type RM Length L Ch R = 1 ,22235.7 ,316.151,321.21,326.269
XS GIS Cut Line= 3
     1732235.743      351623.535      1731790.91      351519.501
     1731294.778      351317.678
#Sta/Elev= 30
       0  1102.8    77.8  1080.6   106.9 1069.25   126.4 1059.03   145.8 1053.12
   194.4 1027.92   204.1 1024.97   223.6 1010.39   233.3 1008.61   252.7  996.56
   262.4  994.47     311  993.79   330.5  990.81   359.6  990.81   388.8  987.53
   495.8  987.53   520.9  984.96     525   984.9   535.9  986.39   622.4  999.04
   680.8 1033.42   700.3 1048.15     749  1070.5   787.9 1078.68   836.6 1097.14
   885.3 1109.07   924.3 1123.65     934 1130.16   943.8 1131.97   992.4  1153.5
#Mann= 3 , 0 , 0
       0      .1       0   520.9    .045       0   535.9      .1       0
Bank Sta=520.9,535.9
XS Rating Curve= 0 ,0
Exp/Cntr=0.3,0.1

Type RM Length L Ch R = 1 ,21914.5 ,340.087,335.165,330.243
XS GIS Cut Line= 3
     1732274.648       351334.93     1731830.371       351221.75
      1731405.87      350958.131
#Sta/Elev= 30
       0 1118.28    19.5 1109.33    87.8 1090.39   136.6 1067.94   185.3 1050.91
   204.8 1035.86   224.4 1026.56   234.1 1018.12   253.6 1009.29   263.4 1002.33
   282.9  996.16   331.7  990.81   390.2  990.81   419.4  987.64   505.5  984.52
   507.5  984.32   520.5  985.97   605.4  997.11   664.2 1033.01   713.2 1049.96
   752.4 1059.96   781.8 1071.82   791.6 1072.07   811.2 1078.77   830.8  1080.6
   840.6 1083.53   850.4    1090   899.4 1095.34   928.8 1104.79   958.2 1108.27
#Mann= 3 , 0 , 0
       0      .1       0   505.5    .045       0   520.5      .1       0
Bank Sta=505.5,520.5
XS Rating Curve= 0 ,0
Exp/Cntr=0.3,0.1

Type RM Length L Ch R = 1 ,21579.4 ,469.383,487.842,506.301
XS GIS Cut Line= 3
     1732412.999      351112.653     1731868.038      350906.062
     1731493.158      350854.045
#Sta/Elev= 30
       0 1077.72    77.7 1059.23    87.4 1058.49   126.3 1045.05   155.4  1038.6
   174.8 1036.61   184.6  1033.5   213.7 1020.37   233.1 1005.51   252.5   995.2
   301.1  990.81     340  990.76   359.4  987.84   456.5  987.45   532.7  981.05
   534.2  980.97   547.7  982.62     641   994.1   660.4  995.11   670.1  997.37
   757.5 1000.88   776.9 1007.43   786.6 1009.05     806 1017.82   815.7  1020.1
   835.1 1029.45   864.2 1034.18   883.6 1034.06   912.8 1037.45   961.3 1049.48
#Mann= 3 , 0 , 0
       0      .1       0   532.7    .045       0   547.7      .1       0
Bank Sta=532.7,547.7
XS Rating Curve= 0 ,0
Exp/Cntr=0.3,0.1

Type RM Length L Ch R = 1 ,21091.5 ,310.139,311.559,312.98
XS GIS Cut Line= 3
     1732535.657      351016.278     1732202.728      350630.782
     1731993.624      350164.446
#Sta/Elev= 30
       0 1092.94    19.6  1088.6      98 1056.66   127.3 1047.93   244.9   991.9
   303.7  990.61   323.2  987.53     431  987.53   460.4  984.32     529  984.25
     552  981.48   558.5  980.97     567  982.05   597.8 1005.38   617.5 1013.14
   637.1 1025.94   656.8 1033.63   686.3 1053.34   705.9 1060.16   764.9 1088.01
   794.4    1098     814  1108.5   823.9 1109.16     873 1123.46   902.5 1138.27
   912.3 1139.34   941.8 1155.99   981.1 1173.33  1000.8 1179.44  1020.4 1189.65
#Mann= 3 , 0 , 0
       0      .1       0     552    .045       0     567      .1       0
Bank Sta=552,567
XS Rating Curve= 0 ,0
Exp/Cntr=0.3,0.1

Type RM Length L Ch R = 1 ,20780   ,791.689,838.795,843.682
XS GIS Cut Line= 3
     1732640.792      350893.621     1732412.999      350367.944
     1732202.728      349964.924
#Sta/Elev= 30
       0 1104.15    19.4 1098.58    48.6 1085.98   106.8 1069.45   126.2  1059.1
   155.4 1050.09   184.5 1037.12   213.6 1013.26   223.3 1010.93   242.8  999.68
   271.9  988.91     369  984.25     437  984.25   466.1  980.97   537.5     981
   543.8  981.05   552.5  983.71   592.3 1003.01   611.6  1010.1   640.6  1035.2
   679.3 1061.29     718 1075.76   737.3 1078.88   785.7 1090.73     805 1098.27
   824.4 1100.21   872.7 1113.68   911.4 1121.69   940.4 1131.21  1027.5 1133.62
#Mann= 3 , 0 , 0
       0      .1       0   537.5    .045       0   552.5      .1       0
Bank Sta=537.5,552.5
XS Rating Curve= 0 ,0
Exp/Cntr=0.3,0.1

Type RM Length L Ch R = 1 ,19941.2 ,556.583,533.671,512.661
XS GIS Cut Line= 3
      1733077.69      350699.719     1732934.862      350239.493
     1732535.657      349842.266
#Sta/Elev= 30
       0 1041.23    49.2 1036.52   108.2  1036.8   167.2 1024.13   186.9 1022.81
   206.5 1015.65   216.4 1015.25   245.9 1001.74   265.5 1000.19     295  990.64
     354   987.3   393.4  981.18   422.9  980.97   449.5  977.31   452.4  977.01
   464.5  977.15   491.6  980.48   540.1  981.28   549.8  983.78   608.1  984.36
   666.4  990.69   734.3  994.36   773.2 1000.25   947.9 1000.77   957.7 1002.31
   977.1 1013.16   986.8 1016.01   996.5 1015.99  1025.6 1026.52    1045 1028.66
#Mann= 3 , 0 , 0
       0      .1       0   449.5    .045       0   464.5      .1       0
Bank Sta=449.5,464.5
XS Rating Curve= 0 ,0
Exp/Cntr=0.3,0.1