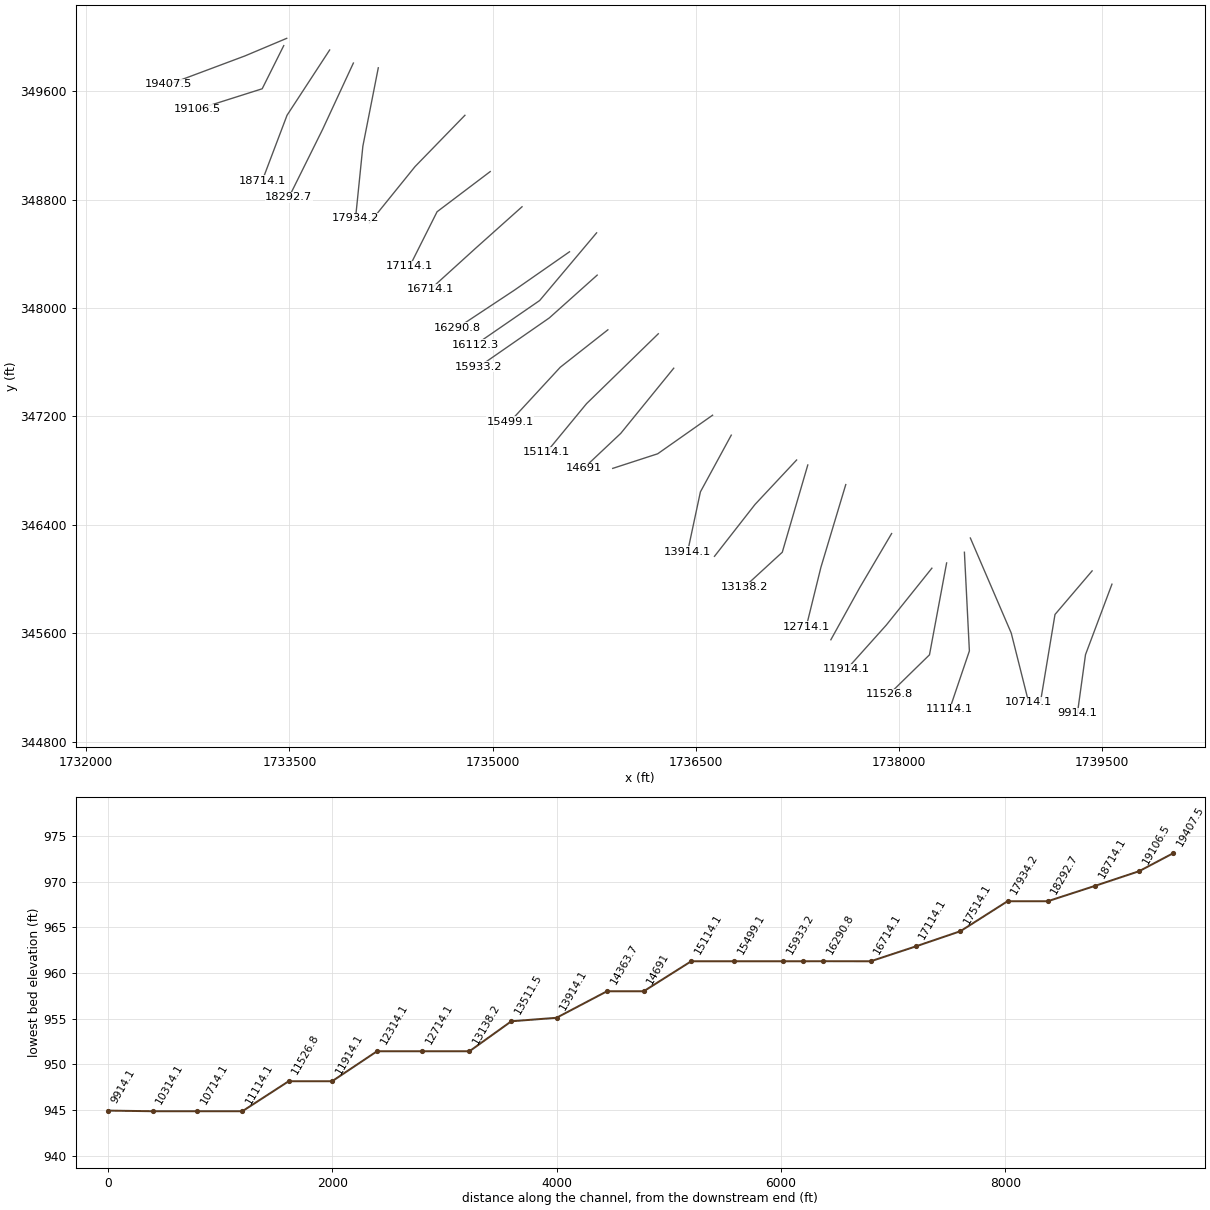
HEC-RAS study LBngmnCrk.prj: LBngmnCrk

--- LBngmnCrk.g01 (geometry) --- (continued)

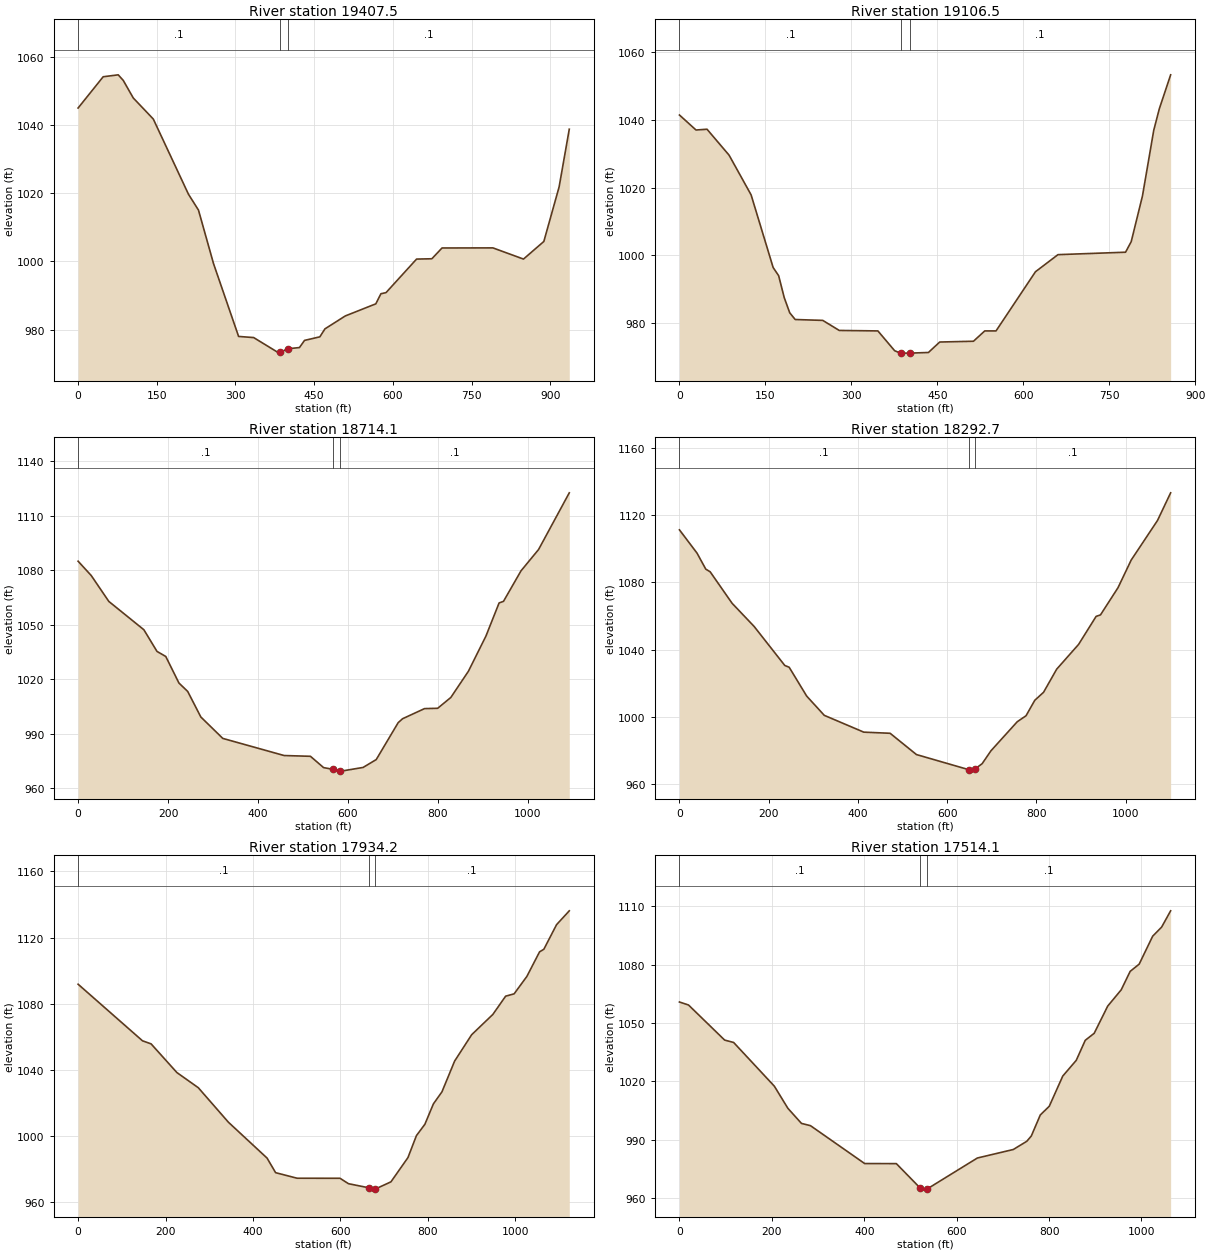
Type RM Length L Ch R = 1 ,19407.5 ,295.298,301.028,302.983
XS GIS Cut Line= 3
     1733480.309      349989.568     1733171.793      349859.795
     1732608.196      349649.085
#Sta/Elev= 30
       0 1044.93    47.8 1054.09    76.5 1054.66    86.1 1053.02   105.2 1047.87
   143.4 1041.69   210.4 1019.66   229.5 1015.01   258.2  999.31     306  977.97
   334.7  977.64   383.2  973.08   384.8  973.27   399.8  974.36     422  974.71
   431.7  976.81   460.9  977.86   470.6  980.19   509.4  983.98   567.6  987.53
   577.3  990.49     587  990.81   645.3 1000.65   674.4 1000.74   693.8  1003.9
   790.8 1003.93   849.1 1000.65   887.9 1005.81     917 1021.79   936.4 1038.72
#Mann= 3 , 0 , 0
       0      .1       0   384.8    .045       0   399.8      .1       0
Bank Sta=384.8,399.8
XS Rating Curve= 0 ,0
Exp/Cntr=0.3,0.1

Type RM Length L Ch R = 1 ,19106.5 ,381.286,392.337,409.13
XS GIS Cut Line= 3
     1733458.272        349935.7     1733299.117      349617.389
     1732821.237      349466.025
#Sta/Elev= 30
       0 1041.47    28.9 1037.04    48.1 1037.27    86.6 1029.61     125  1017.9
   163.5  996.42   173.1  994.01   182.8  987.57   192.4  983.06     202  981.06
   250.1   980.8   278.9  977.83   346.3  977.69   375.5  971.85   385.4  971.13
   386.9  971.13   401.9  971.13   434.5  971.32   454.2  974.41   513.1  974.64
   532.8  977.69   552.5  977.69   621.3  995.17   660.6 1000.22   778.5 1000.94
   788.4 1004.06     808 1017.54   827.7 1036.94   837.5 1043.34   857.2 1053.34
#Mann= 3 , 0 , 0
       0      .1       0   386.9    .045       0   401.9      .1       0
Bank Sta=386.9,401.9
XS Rating Curve= 0 ,0
Exp/Cntr=0.3,0.1

Type RM Length L Ch R = 1 ,18714.1 ,409.359,421.41,425.241
XS GIS Cut Line= 3
     1733797.282      349903.595      1733482.63      349421.974
     1733299.315      348938.295
#Sta/Elev= 30
       0 1085.05    29.3 1077.14    68.3 1062.93   146.3 1047.33   175.5 1035.41
     195 1032.63   224.3 1018.01   243.8 1013.38     273  999.32   321.8  987.54
   458.3  978.11   516.8  977.69     546  971.47   567.8  970.48   582.8  969.59
   585.1  969.53   633.9  971.56   663.1  975.88   711.9  996.19   721.7  998.36
   770.5 1003.93   799.8 1004.11     829 1010.06   868.1 1024.47   907.1 1043.83
   936.4 1062.08   946.2 1062.97   985.2 1079.77  1024.2 1091.48  1092.5 1122.68
#Mann= 3 , 0 , 0
       0      .1       0   567.8    .045       0   582.8      .1       0
Bank Sta=567.8,582.8
XS Rating Curve= 0 ,0
Exp/Cntr=0.3,0.1

Type RM Length L Ch R = 1 ,18292.7 ,350.605,358.54,366.474
XS GIS Cut Line= 3
     1733972.508      349807.221     1733744.714       349316.59
     1733495.662      348815.161
#Sta/Elev= 30
       0 1111.13    39.3 1097.34      59  1087.8    68.8 1086.23     118 1067.52
   167.2 1053.82     236 1030.61   245.9 1029.53   285.2 1012.39   324.6 1000.97
   413.1     991   472.1  990.33   531.1  977.69   648.3  968.72   658.8  967.85
   663.3  969.31   678.4  972.28   698.1  979.93     757  997.17   776.7 1000.74
   796.3  1009.9     816 1014.67   845.4 1028.39   894.5  1043.1   933.8 1059.74
   943.6 1060.64   982.9  1076.8  1012.4 1093.19  1071.3 1116.67  1100.8 1133.12
#Mann= 3 , 0 , 0
       0      .1       0   648.3    .045       0   663.3      .1       0
Bank Sta=648.3,663.3
XS Rating Curve= 0 ,0
Exp/Cntr=0.3,0.1

Type RM Length L Ch R = 1 ,17934.2 ,435.12,420.05,407.048
XS GIS Cut Line= 3
     1734156.495      349772.176     1734042.598      349193.932
     1733988.488      348662.498
#Sta/Elev= 30
       0 1091.78   147.3 1057.55     167 1055.69   225.9 1038.37     275 1029.17
   343.8 1008.32   432.2  986.63   451.8   977.8     501  974.44   599.1  974.41
   618.5  971.13   664.6  968.68   676.8  967.85   679.6  967.87   715.6  972.26
   754.5  986.93   773.9 1000.22   793.3 1007.11   812.7 1019.41   832.2 1026.66
   861.3 1045.31   900.2 1061.23   948.7 1073.51   977.9 1084.54   997.3 1085.95
  1026.4 1096.45  1055.5 1111.34  1065.3 1112.91  1094.4 1127.78  1123.5 1136.16
#Mann= 3 , 0 , 0
       0      .1       0   664.6    .045       0   679.6      .1       0
Bank Sta=664.6,679.6
XS Rating Curve= 0 ,0
Exp/Cntr=0.3,0.1

Type RM Length L Ch R = 1 ,17514.1 ,404.734,400,405.093
XS GIS Cut Line= 3
     1734796.068      349421.725     1734427.844      349043.249
     1734091.381      348627.239
#Sta/Elev= 30
       0 1060.74    19.6  1059.2    97.8 1041.17   117.3 1039.94   205.4 1017.47
   234.7  1006.1     264  998.36   283.6  997.18   400.9  977.71   469.4  977.68
   520.5  965.26     528  964.57   535.5  964.57   644.8  980.56   722.6  984.94
   751.8  989.17   761.5  991.87     781 1002.69   800.4 1007.16   829.6 1022.67
   858.8 1030.76   878.3 1041.06   897.7 1044.67   926.9 1058.64   956.1 1066.99
   975.5 1076.48     995  1080.2  1024.2 1094.55  1043.6 1099.24  1063.1  1107.6
#Mann= 3 , 0 , 0
       0      .1       0   520.5    .045       0   535.5      .1       0
Bank Sta=520.5,535.5
XS Rating Curve= 0 ,0
Exp/Cntr=0.3,0.1

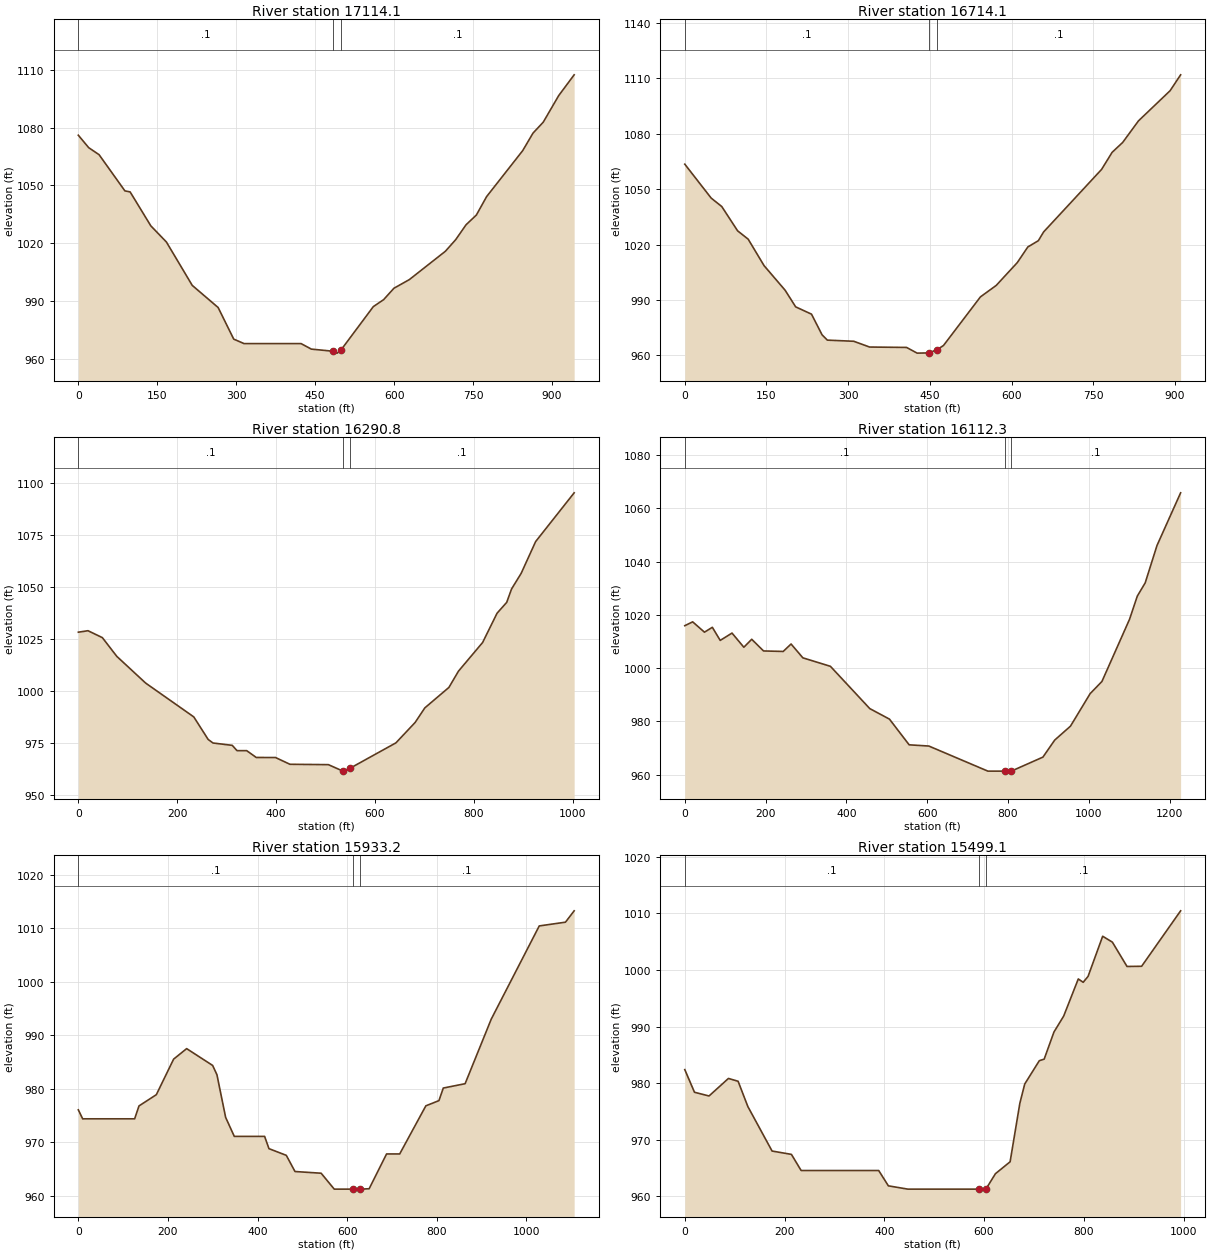
Type RM Length L Ch R = 1 ,17114.1 ,396.559,400,391.713
XS GIS Cut Line= 3
     1734983.049      349006.521     1734590.537         348710.
     1734388.356      348307.969
#Sta/Elev= 30
       0 1076.04    19.7 1069.58    39.4 1065.94    88.5 1047.14    98.4 1046.61
   137.7 1028.99   167.3  1020.6   216.4  998.07   265.6  986.58   295.2  970.17
   314.8  967.85   423.1  967.85   442.7  964.98   484.4  963.87   491.9   962.9
   499.4  964.69   560.4  987.05     580  990.67   599.5  996.58   628.9 1001.09
   697.4 1015.82   716.9 1021.82   736.5 1029.53   756.1 1034.59   775.6 1044.17
   844.1 1068.02   863.7 1077.12   883.2 1082.82   912.6 1096.64   941.9  1107.4
#Mann= 3 , 0 , 0
       0      .1       0   484.4    .045       0   499.4      .1       0
Bank Sta=484.4,499.4
XS Rating Curve= 0 ,0
Exp/Cntr=0.3,0.1

Type RM Length L Ch R = 1 ,16714.1 ,426.585,423.34,419.928
XS GIS Cut Line= 3
     1735217.863      348746.714     1734877.896      348443.143
      1734540.87       348137.67
#Sta/Elev= 30
       0 1063.45    48.5  1045.1    67.9 1040.55      97 1027.41   116.4  1022.9
   145.5 1008.62   184.3  995.27   203.6   986.3   232.7  982.35   252.1  971.18
   261.8  968.31   310.3  967.69   339.4  964.57   407.3  964.36   426.7  961.28
   448.3   961.4   463.3  963.14   475.1  965.41   542.9  991.68   571.9  997.88
   610.6 1010.22     630 1018.69   649.3 1022.08     659 1026.82   765.5 1060.64
   784.8 1069.86   804.2 1075.21   833.2 1086.87   891.3 1103.19   910.6 1111.77
#Mann= 3 , 0 , 0
       0      .1       0   448.3    .045       0   463.3      .1       0
Bank Sta=448.3,463.3
XS Rating Curve= 0 ,0
Exp/Cntr=0.3,0.1

Type RM Length L Ch R = 1 ,16290.8 ,180.218,178.467,176.856
XS GIS Cut Line= 3
     1735568.405      348414.637     1735161.239      348131.235
     1734738.484      347851.851
#Sta/Elev= 30
       0 1028.08    19.5 1028.79    48.6 1025.47    77.8 1016.46   136.2 1003.61
   233.5  987.36   262.6  976.51   272.4  974.81   311.3  973.68     321  971.13
   340.5  971.13   359.9  967.85   398.8  967.83     428  964.58   505.8   964.4
   534.4  961.37   535.1  961.29   549.4  962.66   642.3  974.87   681.2  984.69
   700.7  991.67   749.5 1001.53   768.9 1009.37   817.7 1023.14   846.9 1037.21
   866.4 1042.42   876.1 1048.82   895.6 1056.35   924.9 1071.65  1002.8 1095.08
#Mann= 3 , 0 , 0
       0      .1       0   534.4    .045       0   549.4      .1       0
Bank Sta=534.4,549.4
XS Rating Curve= 0 ,0
Exp/Cntr=0.3,0.1

Type RM Length L Ch R = 1 ,16112.3 ,176.246,179.175,182.616
XS GIS Cut Line= 3
     1735768.571      348554.358     1735348.029      348054.965
     1734874.645      347729.323
#Sta/Elev= 30
       0 1015.91    19.5 1017.35    48.7 1013.47    68.2  1015.3    87.7 1010.38
   116.9 1013.13   146.2 1007.81   165.7  1010.8   194.9 1006.42   243.6 1006.23
   263.1 1009.03   292.3 1003.83   360.5 1000.65     458  984.76   506.7  980.81
   555.4  971.16   604.2   970.7   750.3  961.28   793.3  961.28   808.3  961.28
   886.6  966.54   915.8  972.94   954.8  978.17  1003.5  990.38  1032.7  994.96
  1100.9 1018.26  1120.3 1027.03  1139.8 1031.99    1169 1046.02  1227.5 1065.81
#Mann= 3 , 0 , 0
       0      .1       0   793.3    .045       0   808.3      .1       0
Bank Sta=793.3,808.3
XS Rating Curve= 0 ,0
Exp/Cntr=0.3,0.1

Type RM Length L Ch R = 1 ,15933.2 ,426.708,434.102,440.165
XS GIS Cut Line= 3
     1735772.885      348242.443     1735419.529      347926.755
     1734899.361      347566.225
#Sta/Elev= 30
       0  976.09     9.7  974.41   125.7  974.41   135.4  976.82   174.1  978.92
   212.7  985.56   241.8  987.52   299.8  984.38   309.4  982.64   328.8  974.68
   348.1  971.13   415.8  971.13   425.5  968.84   464.2  967.59   483.6  964.57
     542  964.25   571.2  961.28   613.1  961.28   628.1  961.28   649.1  961.35
     688  967.85   717.3  967.85   775.7  976.84   804.9  977.81   814.6  980.16
   863.3  980.97   921.7  993.04  1028.8 1010.44  1087.3 1011.14  1106.7 1013.26
#Mann= 3 , 0 , 0
       0      .1       0   613.1    .045       0   628.1      .1       0
Bank Sta=613.1,628.1
XS Rating Curve= 0 ,0
Exp/Cntr=0.3,0.1

Type RM Length L Ch R = 1 ,15499.1 ,388.702,384.915,384.454
XS GIS Cut Line= 3
     1735851.807      347838.865     1735500.245      347562.638
     1735128.953      347160.853
#Sta/Elev= 30
       0   982.4    19.4   978.4    48.6  977.74    87.5  980.84   106.9  980.34
   126.4  975.88     175  968.01   213.8  967.42   233.3  964.57   388.8  964.57
   408.2  961.86   447.1  961.28   589.1  961.28   604.1  961.33   622.9  964.01
   652.3  966.11   671.8  976.44   681.6  979.85   710.9  983.98   720.6  984.25
   740.2  989.04   759.7  991.86     789  998.42   798.8  997.83   808.6  998.87
   837.9 1005.97   857.4 1004.92   886.7 1000.63     916 1000.66   994.2 1010.46
#Mann= 3 , 0 , 0
       0      .1       0   589.1    .045       0   604.1      .1       0
Bank Sta=589.1,604.1
XS Rating Curve= 0 ,0
Exp/Cntr=0.3,0.1

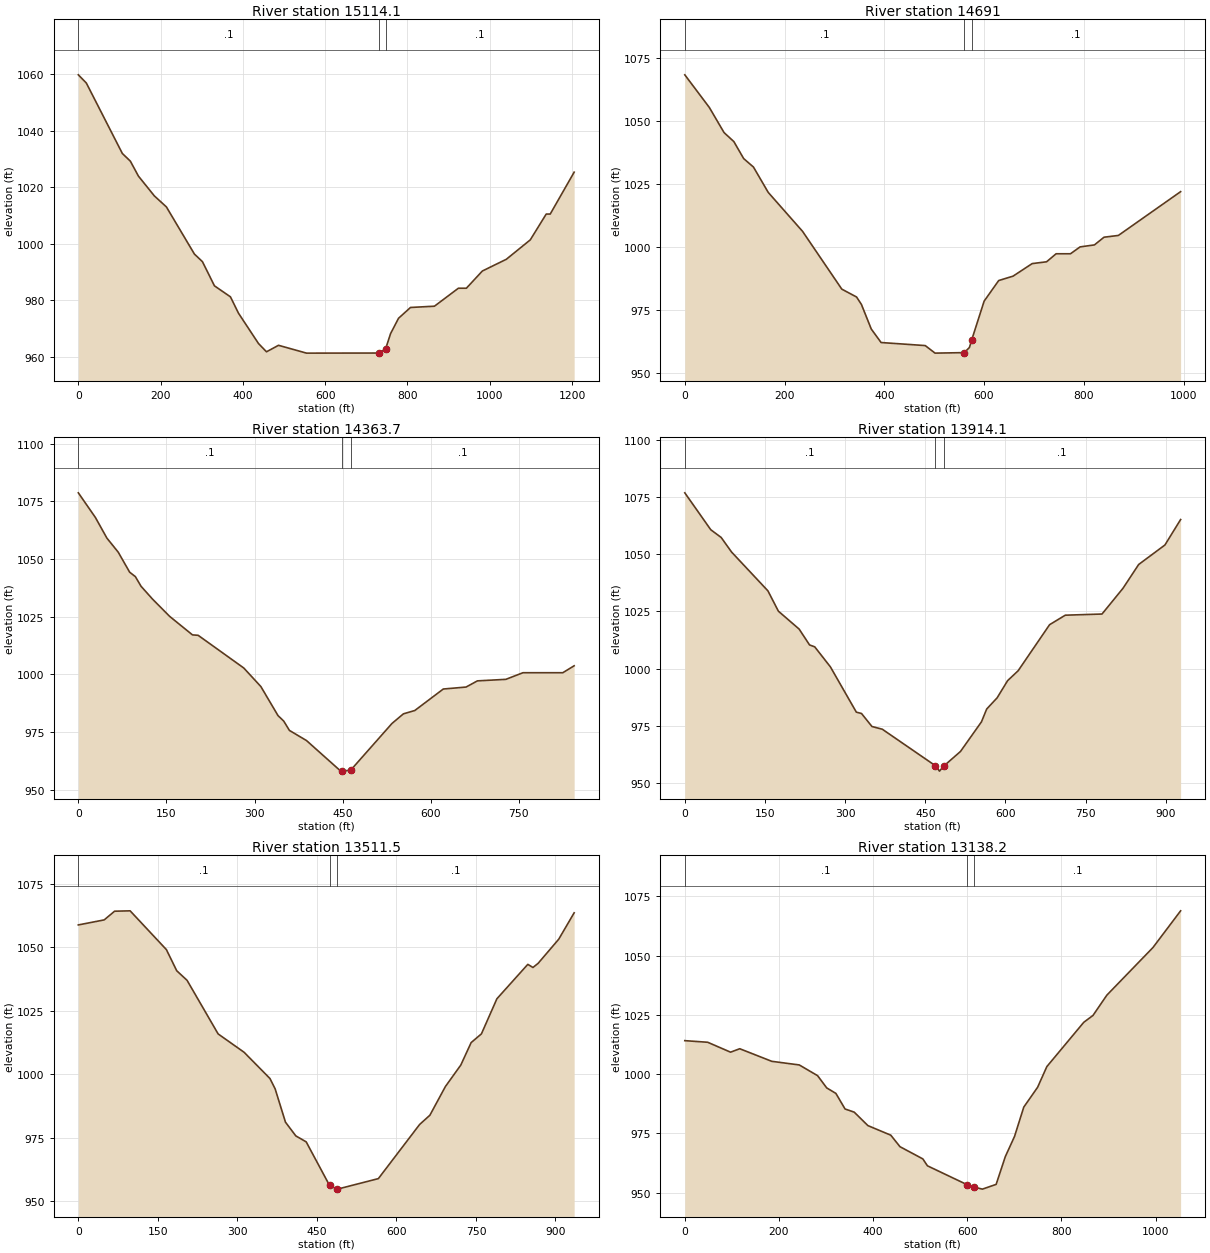
Type RM Length L Ch R = 1 ,15114.1 ,419.245,423.108,423.758
XS GIS Cut Line= 3
     1736224.158      347809.649     1735694.107      347293.837
     1735397.851      346934.547
#Sta/Elev= 30
       0 1059.78    19.5 1056.87     107 1031.94   126.5 1029.22     146 1023.95
   184.9 1016.91   214.1 1013.03   282.2  996.34   301.7  993.65   330.9   985.1
   369.8   981.2   389.3  975.42   437.9  964.69   457.4  961.75   486.6  964.05
   554.7  961.28   732.1  961.31   747.1  962.85     759  968.17   778.4  973.62
   807.5  977.44   865.7  977.89   923.9  984.25   943.3  984.25   982.1  990.34
  1040.4  994.49  1098.6 1001.36  1137.4  1010.5  1147.1  1010.5  1205.3 1025.33
#Mann= 3 , 0 , 0
       0      .1       0   732.1    .045       0   747.1      .1       0
Bank Sta=732.1,747.1
XS Rating Curve= 0 ,0
Exp/Cntr=0.3,0.1

Type RM Length L Ch R = 1 ,14691   ,333.258,327.321,321.247
XS GIS Cut Line= 3
     1736338.054      347555.571     1735946.872      347074.756
     1735674.232       346818.26
#Sta/Elev= 30
       0 1068.27    49.2 1055.34    78.7 1045.39    98.4 1041.81   118.1 1035.07
   137.7 1031.73   167.3 1021.68   236.1 1006.26   314.8  983.36   344.4  980.24
   354.2  977.28   373.9  967.55   393.6   962.2   482.1  960.99   501.8     958
   560.3   958.2   570.7  960.22   575.3  963.24   600.2  978.59   629.4  986.76
   658.2   988.5   696.6  993.48   725.4  994.19   744.6  997.37   773.4  997.37
   792.6 1000.09   821.4 1000.88   840.6 1003.93   869.4 1004.63   994.2 1021.98
#Mann= 3 , 0 , 0
       0      .1       0   560.3    .045       0   575.3      .1       0
Bank Sta=560.3,575.3
XS Rating Curve= 0 ,0
Exp/Cntr=0.3,0.1

Type RM Length L Ch R = 1 ,14363.7 ,439.165,449.571,466.641
XS GIS Cut Line= 3
      1736624.94      347208.744     1736219.511      346924.087
      1735887.68      346816.466
#Sta/Elev= 30
       0 1078.63    29.1 1067.93    48.6 1059.02      68 1052.88    87.4 1044.23
    97.1 1042.31   106.8 1038.12   126.3 1032.57   155.4  1025.1   194.3 1017.06
     204 1016.87   281.7  1002.7   310.8  994.65     340  982.06   349.7   979.7
   359.4  975.65   388.5  971.25   446.8     958   448.7     958   463.7  958.41
   534.1  978.68   553.5  982.83   572.9  984.28   621.4  993.59   660.1  994.44
   679.5  997.12   727.9  997.78     757 1000.65   824.8 1000.65   844.2 1003.66
#Mann= 3 , 0 , 0
       0      .1       0   448.7    .045       0   463.7      .1       0
Bank Sta=448.7,463.7
XS Rating Curve= 0 ,0
Exp/Cntr=0.3,0.1

Type RM Length L Ch R = 1 ,13914.1 ,406.348,402.608,392.204
XS GIS Cut Line= 3
     1736762.996      347061.686     1736535.068      346643.105
     1736440.735      346201.891
#Sta/Elev= 30
       0 1076.96    48.6  1060.8    68.1 1057.41    87.5 1051.04   155.6 1034.02
   175.1 1025.15     214 1017.29   233.4 1010.37   243.2 1009.51   272.4 1000.77
     321  980.92   330.7  980.33   350.2  974.64   369.6  973.45   469.1  957.44
   476.6   955.1   484.1  957.22   515.8  963.69   555.1  976.67   564.9  982.29
   584.5  987.21   604.1  994.73   623.7  999.03   682.6 1019.22     712 1023.38
   780.7 1023.89   819.9 1035.14   849.3 1045.58   898.4 1054.11   927.8 1065.26
#Mann= 3 , 0 , 0
       0      .1       0   469.1    .045       0   484.1      .1       0
Bank Sta=469.1,484.1
XS Rating Curve= 0 ,0
Exp/Cntr=0.3,0.1

Type RM Length L Ch R = 1 ,13511.5 ,364.644,373.324,382.005
XS GIS Cut Line= 3
     1737245.437      346878.169     1736938.285      346550.226
     1736638.926      346167.493
#Sta/Elev= 30
       0 1058.72    48.8  1060.7    68.4 1064.12    97.7 1064.27   166.1    1049
   185.6 1040.68   205.1 1036.91   263.7 1015.81   312.6  1008.6   361.4  998.27
   371.2   994.2   390.7  981.08   410.2  975.68   429.8  973.32   473.8  956.19
   488.2  954.72   488.8  954.72   565.9  958.86   643.7  980.16   663.1  983.81
   692.3  995.09   721.4 1003.56   740.9  1012.4   760.3 1015.84   789.5 1029.66
   847.8  1043.2   857.5 1041.97   867.2 1043.59   906.1  1053.1   935.2 1063.49
#Mann= 3 , 0 , 0
       0      .1       0   473.8    .045       0   488.8      .1       0
Bank Sta=473.8,488.8
XS Rating Curve= 0 ,0
Exp/Cntr=0.3,0.1

Type RM Length L Ch R = 1 ,13138.2 ,426.047,424.067,415.762
XS GIS Cut Line= 3
     1737328.007      346841.578     1737139.671      346197.646
     1736858.062      345939.355
#Sta/Elev= 30
       0 1014.09    48.6 1013.41    97.2 1009.23   116.7 1010.68   184.7 1005.37
   243.1 1003.84     282  999.32   301.4  994.15   320.9  991.83   340.3  985.26
   359.8  983.92   388.9  978.24   437.5   974.2     457  969.35   505.6  964.18
   515.3  961.28   599.9  953.28   614.9  952.28     632  951.44   661.2  953.44
   680.7  965.16   700.3  973.69   719.9  986.05   749.3  994.42   768.9 1003.14
   847.3 1021.83   866.9 1024.73   896.3 1033.28   994.2 1053.37    1053 1068.87
#Mann= 3 , 0 , 0
       0      .1       0   599.9    .045       0   614.9      .1       0
Bank Sta=599.9,614.9
XS Rating Curve= 0 ,0
Exp/Cntr=0.3,0.1

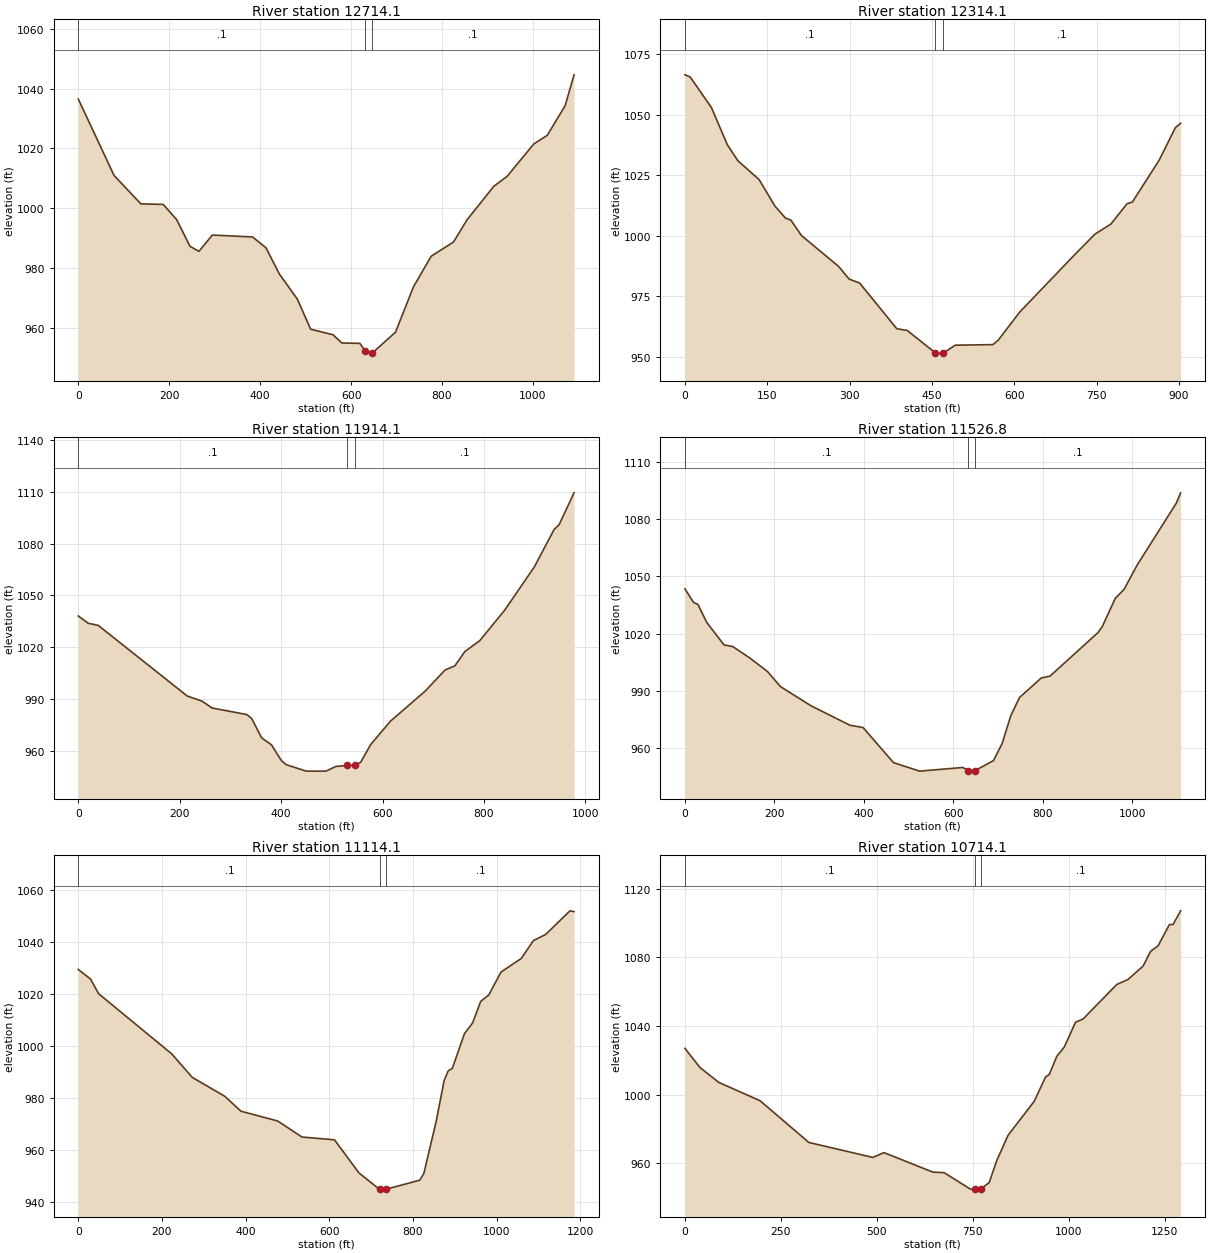
Type RM Length L Ch R = 1 ,12714.1 ,403.874,400,387.985
XS GIS Cut Line= 3
      1737608.44      346696.966     1737424.582      346085.299
     1737316.452      345646.804
#Sta/Elev= 30
       0 1036.55    78.6 1010.96   137.6 1001.45   186.7 1001.27   216.2   996.2
   245.7  987.21   265.3  985.54   294.8     991   383.2  990.36   412.7  986.75
   442.2  977.94   481.5   969.6     511  959.46   560.1   957.6   579.7  954.83
     619  954.72   631.2  952.19   638.7  951.44   646.2  951.44   697.6  958.44
   736.9  973.56   776.2  983.92   825.2  988.66   854.7  996.04   913.6  1007.3
   943.1 1010.67    1002 1021.54  1031.4 1024.41  1070.7 1034.31  1090.3 1044.68
#Mann= 3 , 0 , 0
       0      .1       0   631.2    .045       0   646.2      .1       0
Bank Sta=631.2,646.2
XS Rating Curve= 0 ,0
Exp/Cntr=0.3,0.1

Type RM Length L Ch R = 1 ,12314.1 ,400.9,400,395.688
XS GIS Cut Line= 3
     1737946.951      346335.466     1737711.552      345936.636
     1737498.407       345551.92
#Sta/Elev= 30
       0 1066.53     9.6 1065.65    48.2 1053.03    77.2 1037.65    96.5 1031.01
   135.1 1023.21     164 1012.23   183.3 1007.27     193 1006.46   212.3 1000.07
   279.8  987.33   299.1  982.07   318.4  980.39   385.9  961.54   405.2  960.78
   455.6  951.64   463.1  951.44   470.6  951.44   492.4  954.72   560.9  954.96
   570.6  956.77   609.7  968.39   707.5  991.58   746.6  1000.6   775.9 1004.82
   805.2 1013.18     815 1013.92   863.8 1031.23   893.2 1044.65   902.9 1046.48
#Mann= 3 , 0 , 0
       0      .1       0   455.6    .045       0   470.6      .1       0
Bank Sta=455.6,470.6
XS Rating Curve= 0 ,0
Exp/Cntr=0.3,0.1

Type RM Length L Ch R = 1 ,11914.1 ,376.887,387.363,399.08
XS GIS Cut Line= 3
     1738244.318      346079.951     1737908.182      345660.749
     1737614.125      345332.807
#Sta/Elev= 30
       0 1038.11    19.5 1033.88    39.1  1032.7   214.9  991.69   244.2  988.72
   263.8  984.77   332.2  980.97   341.9  978.71   361.5  967.49     381  963.41
   400.6  954.26   410.3  951.89   449.4  948.16   488.5  948.16     508  950.88
   529.8  951.44   544.8   951.5   556.9  953.26   576.5   963.5   615.6  977.09
   684.1  994.53   723.3 1006.77   742.9 1009.25   762.5 1017.51   791.8  1023.8
   840.8 1041.39   899.5 1066.56   938.6  1088.3   948.4 1091.04   977.8 1109.51
#Mann= 3 , 0 , 0
       0      .1       0   529.8    .045       0   544.8      .1       0
Bank Sta=529.8,544.8
XS Rating Curve= 0 ,0
Exp/Cntr=0.3,0.1

Type RM Length L Ch R = 1 ,11526.8 ,404.342,412.637,409.235
XS GIS Cut Line= 3
     1738353.149      346118.721     1738226.642      345440.712
     1737927.097      345148.341
#Sta/Elev= 30
       0 1043.48    19.4 1036.37    29.1 1035.32    48.6 1025.99    87.4 1014.15
   106.9 1013.32   145.7 1007.22   184.6 1000.25   213.7  992.35   281.7  982.36
   369.1  972.15   398.3  970.96   466.3  952.61   524.6  948.16   621.7  950.07
   632.5  948.48   647.5  948.29   689.7  953.63   709.2  962.58   728.6  977.17
   748.1  986.64   796.8  996.89   816.3  997.84   923.3 1020.56   933.1 1023.72
   962.3 1038.56   981.7 1043.13  1010.9 1055.84  1098.6 1088.29  1108.3 1093.69
#Mann= 3 , 0 , 0
       0      .1       0   632.5    .045       0   647.5      .1       0
Bank Sta=632.5,647.5
XS Rating Curve= 0 ,0
Exp/Cntr=0.3,0.1

Type RM Length L Ch R = 1 ,11114.1 ,397.347,400,407.521
XS GIS Cut Line= 3
     1738484.569      346197.573     1738521.296      345469.442
     1738374.852      345037.811
#Sta/Elev= 30
       0 1029.48    29.2 1025.77    48.6 1020.13   223.6  996.92   272.2  987.94
   349.9  980.65   388.8  974.88   476.3  971.13   534.6  964.95   612.4  963.86
   670.7  951.14   719.3  944.88   721.6  944.88   736.6  944.88   816.3  948.34
     826  950.99   855.1  970.77   874.5  986.75   884.2  990.45   893.9  991.37
     923 1004.76   942.4 1008.86   961.8 1017.18   981.2 1019.67  1010.3 1028.48
  1058.8 1033.72  1087.9 1040.62    1117 1042.95  1175.2 1052.06  1184.9 1051.75
#Mann= 3 , 0 , 0
       0      .1       0   721.6    .045       0   736.6      .1       0
Bank Sta=721.6,736.6
XS Rating Curve= 0 ,0
Exp/Cntr=0.3,0.1

Type RM Length L Ch R = 1 ,10714.1 ,422.897,400,400.171
XS GIS Cut Line= 3
     1738528.375      346302.708     1738830.329      345601.219
      1738959.22      345089.004
#Sta/Elev= 30
       0 1026.94    39.2 1015.78    88.1 1007.13   195.8  996.42   323.1  972.08
   489.6  963.37   518.9  966.16   646.2   954.8   675.6  954.47   744.1  944.88
   756.2  944.88   771.2  944.99   793.1  948.73   812.6  961.43     842  976.23
   910.4  996.09   939.8 1010.22   949.6 1011.72   969.1 1022.26   988.7 1027.73
    1018 1042.19  1037.6 1044.05  1125.6  1064.2    1155 1067.13  1194.1 1074.92
  1213.7 1083.52  1233.2 1086.75  1262.6 1099.07  1272.3  1099.2  1291.9 1107.12
#Mann= 3 , 0 , 0
       0      .1       0   756.2    .045       0   771.2      .1       0
Bank Sta=756.2,771.2
XS Rating Curve= 0 ,0
Exp/Cntr=0.3,0.1

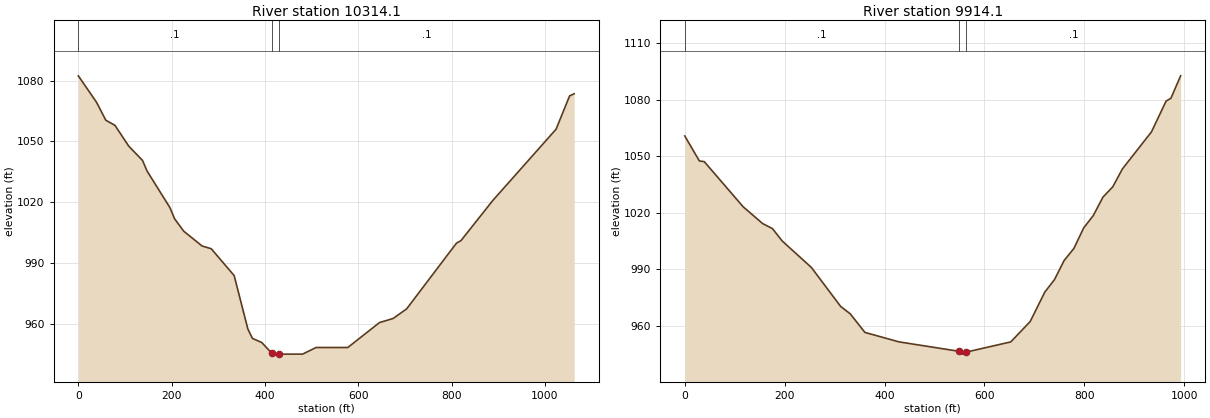
Type RM Length L Ch R = 1 ,10314.1 ,392.156,400,396.434
XS GIS Cut Line= 3
     1739427.507      346059.855     1739153.492       345738.49
     1739048.535      345107.003
#Sta/Elev= 30
       0 1082.37    39.3  1069.2    58.9 1060.44    78.6 1057.89     108 1047.63
   137.5 1040.59   147.3 1035.33   196.4 1017.22   206.3 1011.75   225.9 1005.61
   265.2   998.3   284.8  996.95   333.9   983.7   363.4  957.21   373.2  952.63
   392.9  950.64   414.8  945.27   429.8  944.88   480.5  944.88   509.6  948.16
   577.5  948.16   645.4  960.48   674.5  962.48   703.6  967.25   810.3  999.71
     820 1000.96   887.9 1020.72  1023.7 1055.98  1052.8 1072.48  1062.5  1073.5
#Mann= 3 , 0 , 0
       0      .1       0   414.8    .045       0   429.8      .1       0
Bank Sta=414.8,429.8
XS Rating Curve= 0 ,0
Exp/Cntr=0.3,0.1

Type RM Length L Ch R = 1 ,9914.1  ,397.494,400,393.985
XS GIS Cut Line= 3
     1739574.036      345962.036     1739378.686      345441.833
     1739318.952      345008.698
#Sta/Elev= 30
       0 1060.68    29.2 1047.43      39 1047.07     117 1023.08     156  1014.2
   175.5 1011.55     195 1004.99   253.5  990.93     312  970.29   331.5  966.27
   360.7  956.47   428.9  951.45   548.2  946.49   555.7  944.95   563.2  946.01
   652.8  951.44   691.7  962.26   720.9  977.84   740.3  984.47   759.7  994.65
   779.1 1000.99   798.6 1011.82     818 1018.46   837.4 1028.26   856.9 1033.66
   876.3 1043.19   934.6 1062.89   963.8 1079.19   973.5  1080.7   992.9 1092.59
#Mann= 3 , 0 , 0
       0      .1       0   548.2    .045       0   563.2      .1       0
Bank Sta=548.2,563.2
XS Rating Curve= 0 ,0
Exp/Cntr=0.3,0.1