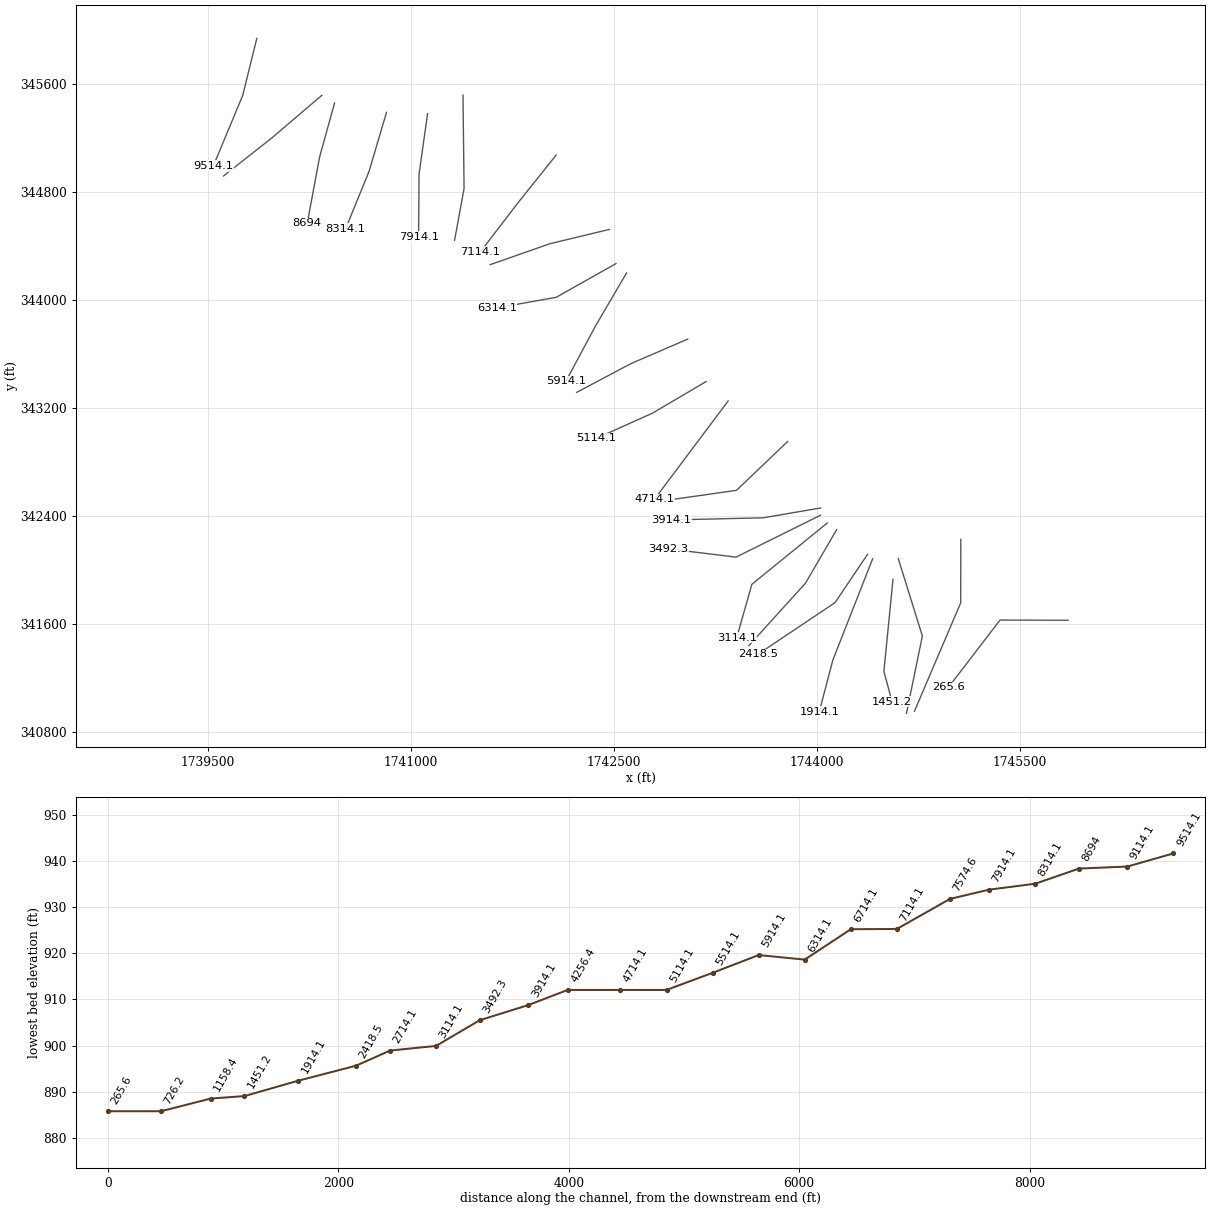
HEC-RAS study LBngmnCrk.prj: LBngmnCrk

--- LBngmnCrk.g01 (geometry) --- (continued)

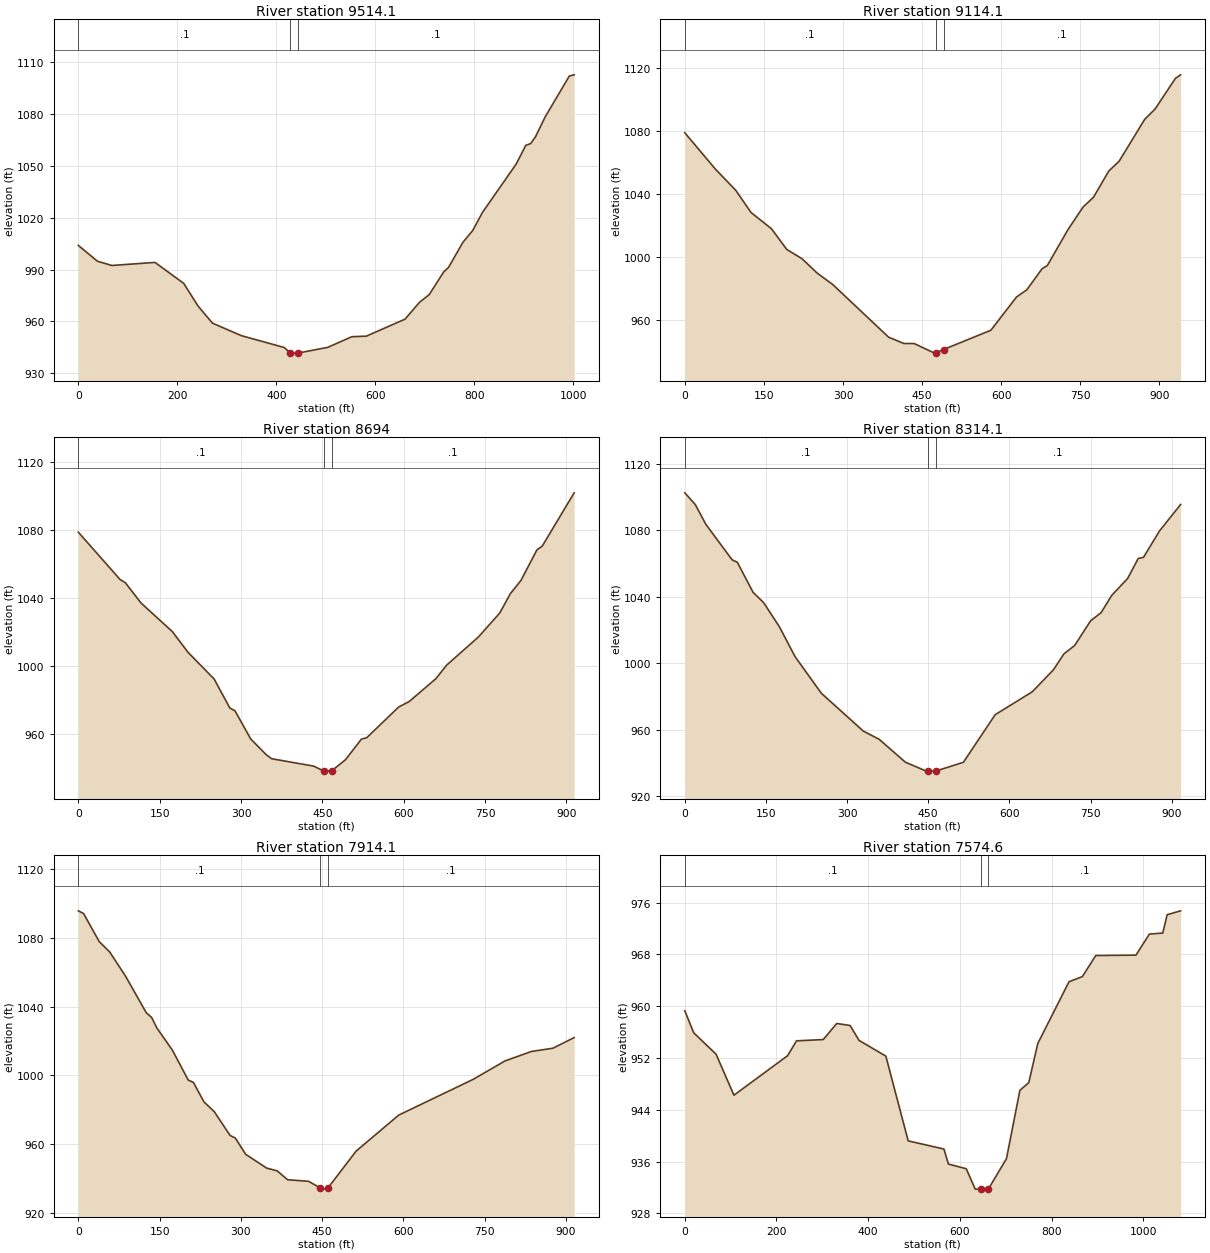
Type RM Length L Ch R = 1 ,9514.1  ,414,400,388.486
XS GIS Cut Line= 3
     1739861.297      345934.654     1739756.907      345511.969
     1739539.692      344989.146
#Sta/Elev= 30
       0 1003.99    38.7  994.82    67.7  992.37   154.8  994.15   212.9     982
   241.9  968.84   270.9  958.98     329  951.75     416  944.84   427.9  941.68
   435.4   941.6   442.9   941.6   503.7  944.93   552.5  951.11   581.8  951.44
   659.9  961.28   689.2  971.05   708.7  975.48     738  988.64   747.7  991.24
     777 1005.86   796.6 1012.62   816.1 1023.01   884.4 1051.13   903.9 1061.98
   913.7 1062.98   923.4 1066.93     943 1078.46   991.8 1102.13  1001.5 1102.81
#Mann= 3 , 0 , 0
       0      .1       0   427.9    .045       0   442.9      .1       0
Bank Sta=427.9,442.9
XS Rating Curve= 0 ,0
Exp/Cntr=0.3,0.1

Type RM Length L Ch R = 1 ,9114.1  ,405.027,420.184,436.294
XS GIS Cut Line= 3
     1740341.574      345512.657     1739974.225      345198.834
     1739615.495      344915.751
#Sta/Elev= 30
       0 1078.99      58 1055.88    96.6 1042.41   125.6 1028.25   164.3 1017.94
   193.3 1004.76   222.2  998.84   251.2  989.64   280.2  982.52   386.5  948.89
   415.5  944.88   434.8  944.88   473.5  938.76   475.6  938.93   490.6  941.06
   580.4  953.34     629   974.5   648.4  979.03   677.6  992.55   687.3  994.46
   726.2 1017.16   745.7 1027.01   755.4 1031.83   774.8 1037.91     804 1054.71
   823.4 1060.83   872.1  1087.6   891.5 1094.04   930.4 1113.68   940.1 1115.87
#Mann= 3 , 0 , 0
       0      .1       0   475.6    .045       0   490.6      .1       0
Bank Sta=475.6,490.6
XS Rating Curve= 0 ,0
Exp/Cntr=0.3,0.1

Type RM Length L Ch R = 1 ,8694    ,382.116,379.816,375.237
XS GIS Cut Line= 3
     1740435.797      345456.108      1740325.25      345056.864
     1740233.662      344565.087
#Sta/Elev= 30
       0 1078.58    77.1 1050.77    86.7 1048.94   115.6 1037.02   173.4 1020.24
   202.3 1008.07   250.5  992.38   279.4   975.4     289  973.71   317.9  957.22
   346.8  947.88   356.5   945.6   433.9  941.27     453  938.35   453.5  938.32
     468  938.67   492.7     945   522.2  957.11     532  957.95   590.8  975.94
   610.4  979.22   659.5  992.59   679.1 1000.48   737.9 1017.06   777.2 1031.11
   796.8 1042.48   816.4 1050.28   845.8  1068.2   855.6 1070.39   914.5 1101.69
#Mann= 3 , 0 , 0
       0      .1       0     453    .045       0     468      .1       0
Bank Sta=453,468
XS Rating Curve= 0 ,0
Exp/Cntr=0.3,0.1

Type RM Length L Ch R = 1 ,8314.1  ,396.169,400,409.132
XS GIS Cut Line= 3
     1740819.448      345386.425     1740690.146      344948.894
     1740516.675      344522.622
#Sta/Elev= 30
       0  1102.6    19.4 1095.54    38.8 1083.69    87.4 1062.28    97.1  1060.8
   126.2 1042.69   145.6 1036.54   174.7 1022.06   203.9 1003.93   252.4  981.94
     330  959.13   359.2  954.23   407.7  940.42   446.5  935.04   448.7  935.04
   463.7  935.04     515  940.37   573.7  969.01   642.3  982.81   681.5  996.09
     701 1005.71   720.6 1010.66     750 1025.51   769.6 1030.49   789.2 1040.86
   818.5 1051.01   838.1 1063.06   847.9 1063.78   877.3 1079.57   916.5 1095.59
#Mann= 3 , 0 , 0
       0      .1       0   448.7    .045       0   463.7      .1       0
Bank Sta=448.7,463.7
XS Rating Curve= 0 ,0
Exp/Cntr=0.3,0.1

Type RM Length L Ch R = 1 ,7914.1  ,335.946,339.516,340.064
XS GIS Cut Line= 3
      1741122.83      345376.511     1741059.625      344927.039
     1741056.759      344465.781
#Sta/Elev= 30
       0 1095.76     9.7 1094.18    38.6 1077.83    57.9 1071.81    86.9 1057.85
   125.5  1036.4   135.2 1033.72   144.9 1027.62   173.8 1014.57   202.8  997.27
   212.5  995.84   231.8  984.58   251.1  978.78   280.1  965.01   289.7   963.5
     309  954.01   347.7  945.99     367   944.4   386.3  939.23   424.9  938.31
   446.4  934.49   453.9  933.76   461.4  934.69   512.8  955.91   591.3  976.84
   728.7  997.64   787.6 1008.39   836.6 1013.92   875.9 1015.77   915.2 1021.98
#Mann= 3 , 0 , 0
       0      .1       0   446.4    .045       0   461.4      .1       0
Bank Sta=446.4,461.4
XS Rating Curve= 0 ,0
Exp/Cntr=0.3,0.1

Type RM Length L Ch R = 1 ,7574.6  ,475.52,460.484,445.902
XS GIS Cut Line= 3
     1741384.554      345514.192     1741392.572      344822.241
     1741322.411      344439.056
#Sta/Elev= 30
       0   959.3    19.5  955.89    68.2  952.59   107.2  946.26   224.2  952.35
   243.7  954.65   302.1  954.85   331.4  957.33   360.6  957.02   380.1  954.72
   438.6  952.29   487.3  939.21   565.3  937.95     575  935.63     614  934.91
   633.5  931.76   647.1  931.76   662.1  931.76   701.7  936.46     731  947.01
   750.4   948.2   769.9  954.22   838.1  963.77   867.3  964.57   896.5  967.82
   984.2  967.88  1013.4  971.13  1042.6  971.29  1052.3  974.12  1081.6  974.72
#Mann= 3 , 0 , 0
       0      .1       0   647.1    .045       0   662.1      .1       0
Bank Sta=647.1,662.1
XS Rating Curve= 0 ,0
Exp/Cntr=0.3,0.1

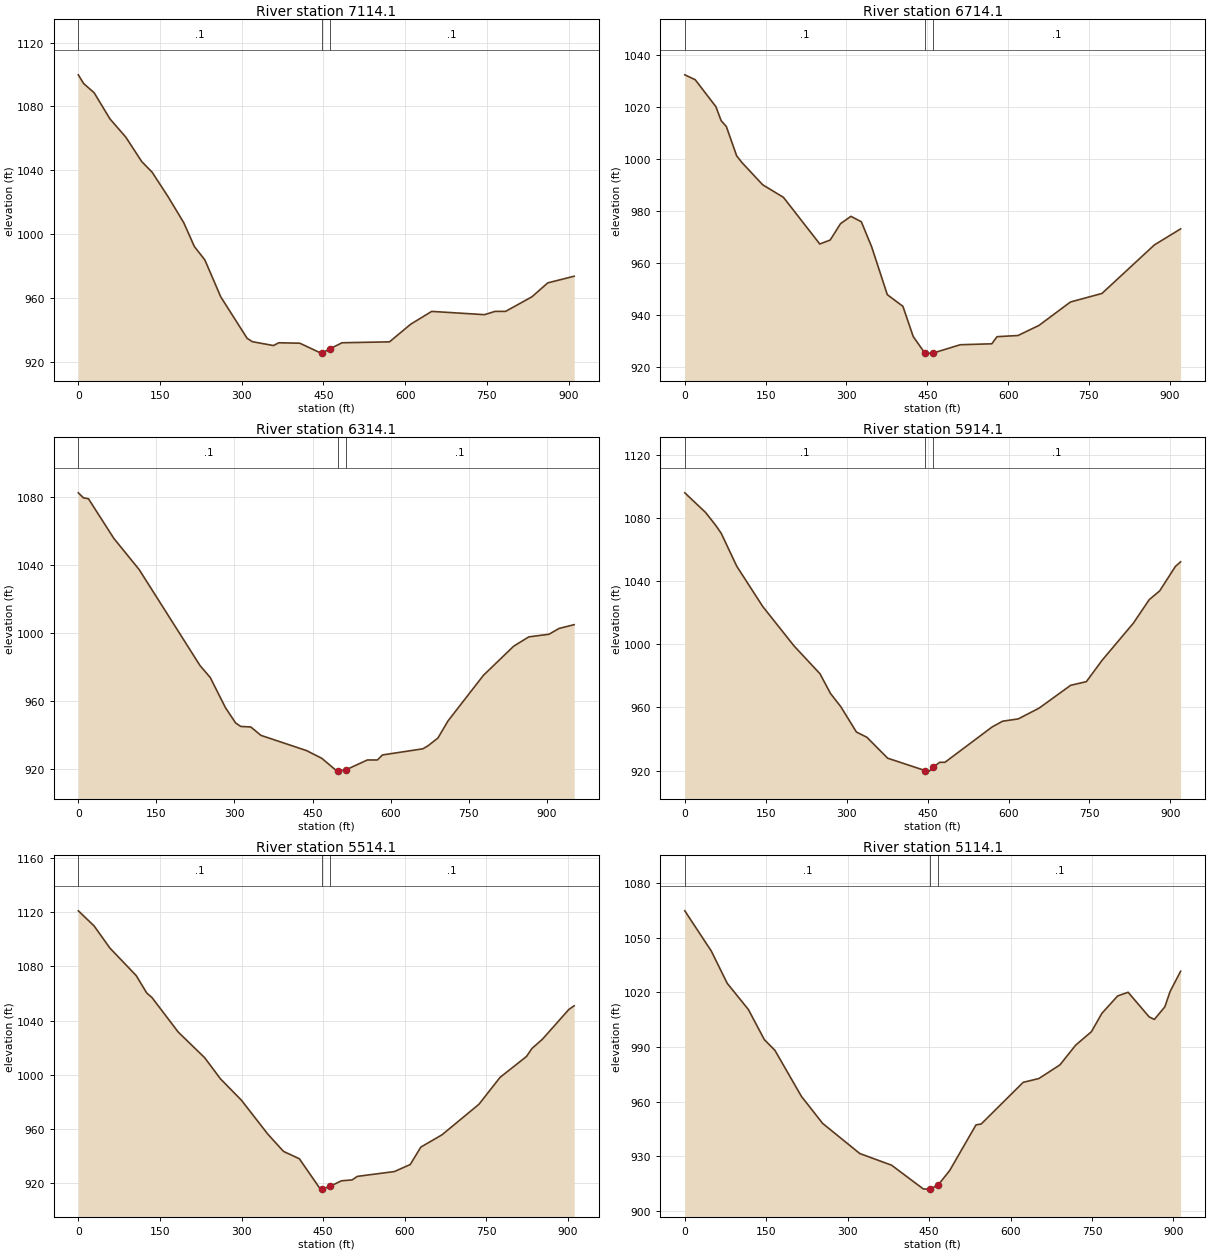
Type RM Length L Ch R = 1 ,7114.1  ,415.012,400,386.81
XS GIS Cut Line= 3
     1742072.989      345070.428     1741789.292      344714.727
     1741512.733      344353.282
#Sta/Elev= 30
       0  1099.8     9.7 1094.35      29 1088.58    58.1 1072.14    87.1 1060.75
   116.2 1045.48   135.5 1038.71   164.6 1023.44   193.6 1007.01     213  992.12
   232.3  983.69   261.4  960.58   309.8  934.56   319.5  932.43   358.2  930.01
   367.9  931.76   406.6  931.48   445.3  925.26   447.5  925.41   462.5  928.06
     484  931.76   571.2  932.34   609.9  943.36   648.6  951.44   745.5  949.38
   764.8  951.44   784.2  951.44   832.6  960.58   861.7  969.32   910.1  973.49
#Mann= 3 , 0 , 0
       0      .1       0   447.5    .045       0   462.5      .1       0
Bank Sta=447.5,462.5
XS Rating Curve= 0 ,0
Exp/Cntr=0.3,0.1

Type RM Length L Ch R = 1 ,6714.1  ,393.445,400,396.39
XS GIS Cut Line= 3
     1742467.132      344520.055     1742026.932      344413.843
     1741586.009       344259.11
#Sta/Elev= 30
       0 1032.29    19.3 1030.42    57.8 1020.01    67.4 1014.67    77.1 1012.39
    96.3 1001.09     106  998.55   144.5  989.99   183.1  985.14   250.5   967.2
   269.8  968.71     289  975.03   308.3  977.84   327.6  975.75   346.9  966.03
   375.8   947.7   404.7  943.22   423.9  931.57   445.3  925.27   452.8   925.2
   460.3   925.2   511.2  928.43   569.7  928.79   579.4  931.53   618.3  931.98
   657.3  935.87   715.7  944.88   774.1  948.16   871.4  966.84   920.1  973.01
#Mann= 3 , 0 , 0
       0      .1       0   445.3    .045       0   460.3      .1       0
Bank Sta=445.3,460.3
XS Rating Curve= 0 ,0
Exp/Cntr=0.3,0.1

Type RM Length L Ch R = 1 ,6314.1  ,388.269,400,420.479
XS GIS Cut Line= 3
      1742514.87      344266.787     1742073.768      344017.279
     1741634.912      343938.548
#Sta/Elev= 30
       0  1082.3     9.7 1079.38    19.5  1078.8    68.2 1055.52   116.9 1037.15
   233.9  980.67   253.4  973.71   282.6  955.98   302.1  946.99   311.9  944.92
   331.4   944.6   350.8  939.67   438.6  930.69   467.8  926.16     497  918.63
   499.3  918.66   514.3  919.42   555.2  925.18   574.6   925.2   584.3  928.14
   661.9  931.76   671.6  933.49   690.9   938.1   710.3  948.18   778.2  974.95
   836.3  992.08   865.4  997.58   904.2  999.12   923.6 1002.54   952.6 1004.76
#Mann= 3 , 0 , 0
       0      .1       0   499.3    .045       0   514.3      .1       0
Bank Sta=499.3,514.3
XS Rating Curve= 0 ,0
Exp/Cntr=0.3,0.1

Type RM Length L Ch R = 1 ,5914.1  ,414.333,400,386.61
XS GIS Cut Line= 3
     1742593.156      344197.286     1742364.476      343806.152
     1742144.813      343395.253
#Sta/Elev= 30
       0  1095.8    38.6 1083.35    57.8 1074.99    67.5 1070.18    96.4 1049.28
   144.6 1023.78   202.4  998.91   250.6  981.24   269.9  968.85   289.2  960.38
   318.1  944.36   337.4  941.06     376   927.8   445.6  919.95   453.1  919.61
   460.6  922.13   472.5   925.2   482.2   925.2   569.6  947.57     589  951.21
   618.1  952.68   656.9  959.54   715.2  973.94   744.3  976.26   773.4  989.75
   831.6 1013.37   860.8 1028.16   880.2 1033.72   909.3  1049.2     919 1052.14
#Mann= 3 , 0 , 0
       0      .1       0   445.6    .045       0   460.6      .1       0
Bank Sta=445.6,460.6
XS Rating Curve= 0 ,0
Exp/Cntr=0.3,0.1

Type RM Length L Ch R = 1 ,5514.1  ,397.16,400,398.526
XS GIS Cut Line= 3
     1743045.397      343707.624      1742628.03      343527.237
     1742224.506      343313.129
#Sta/Elev= 30
       0  1120.9      29 1109.78      58 1093.47   106.4 1073.17   125.8  1060.3
   135.4 1056.98   183.8 1031.47   232.2 1012.68   261.2   997.1   299.9  981.27
   348.3  956.32   377.3  943.55   406.3  938.18     445  915.77   447.2  915.89
   462.2  917.75   483.8  921.91   503.3  922.56     513  925.17     581  928.72
   610.2  933.92   629.6  946.74   668.5  955.79   736.5  978.33   775.4  998.19
     824 1013.58   833.7 1019.36   853.2 1026.28   901.8 1048.21   911.5  1050.9
#Mann= 3 , 0 , 0
       0      .1       0   447.2    .045       0   462.2      .1       0
Bank Sta=447.2,462.2
XS Rating Curve= 0 ,0
Exp/Cntr=0.3,0.1

Type RM Length L Ch R = 1 ,5114.1  ,391.087,400,411.426
XS GIS Cut Line= 3
     1743180.792      343393.123     1742785.651      343159.621
     1742371.298      342973.346
#Sta/Elev= 30
       0  1064.8    48.8 1042.74    78.1 1025.04   117.2 1010.61   146.5  994.12
     166  988.24   214.8  962.98   253.9  948.15   322.3  931.61   380.9   925.2
   439.4  912.16   449.2  912.07   451.5  912.09   466.5  914.28     488  922.32
   536.3   947.3     546  947.83   623.3  970.67   652.3  972.78     691  980.26
     720  991.09     749  998.47   768.3 1008.56   797.3 1018.09   816.6 1020.11
   855.3 1006.61   864.9 1005.19   884.3 1012.14   893.9 1020.53   913.3 1031.65
#Mann= 3 , 0 , 0
       0      .1       0   451.5    .045       0   466.5      .1       0
Bank Sta=451.5,466.5
XS Rating Curve= 0 ,0
Exp/Cntr=0.3,0.1

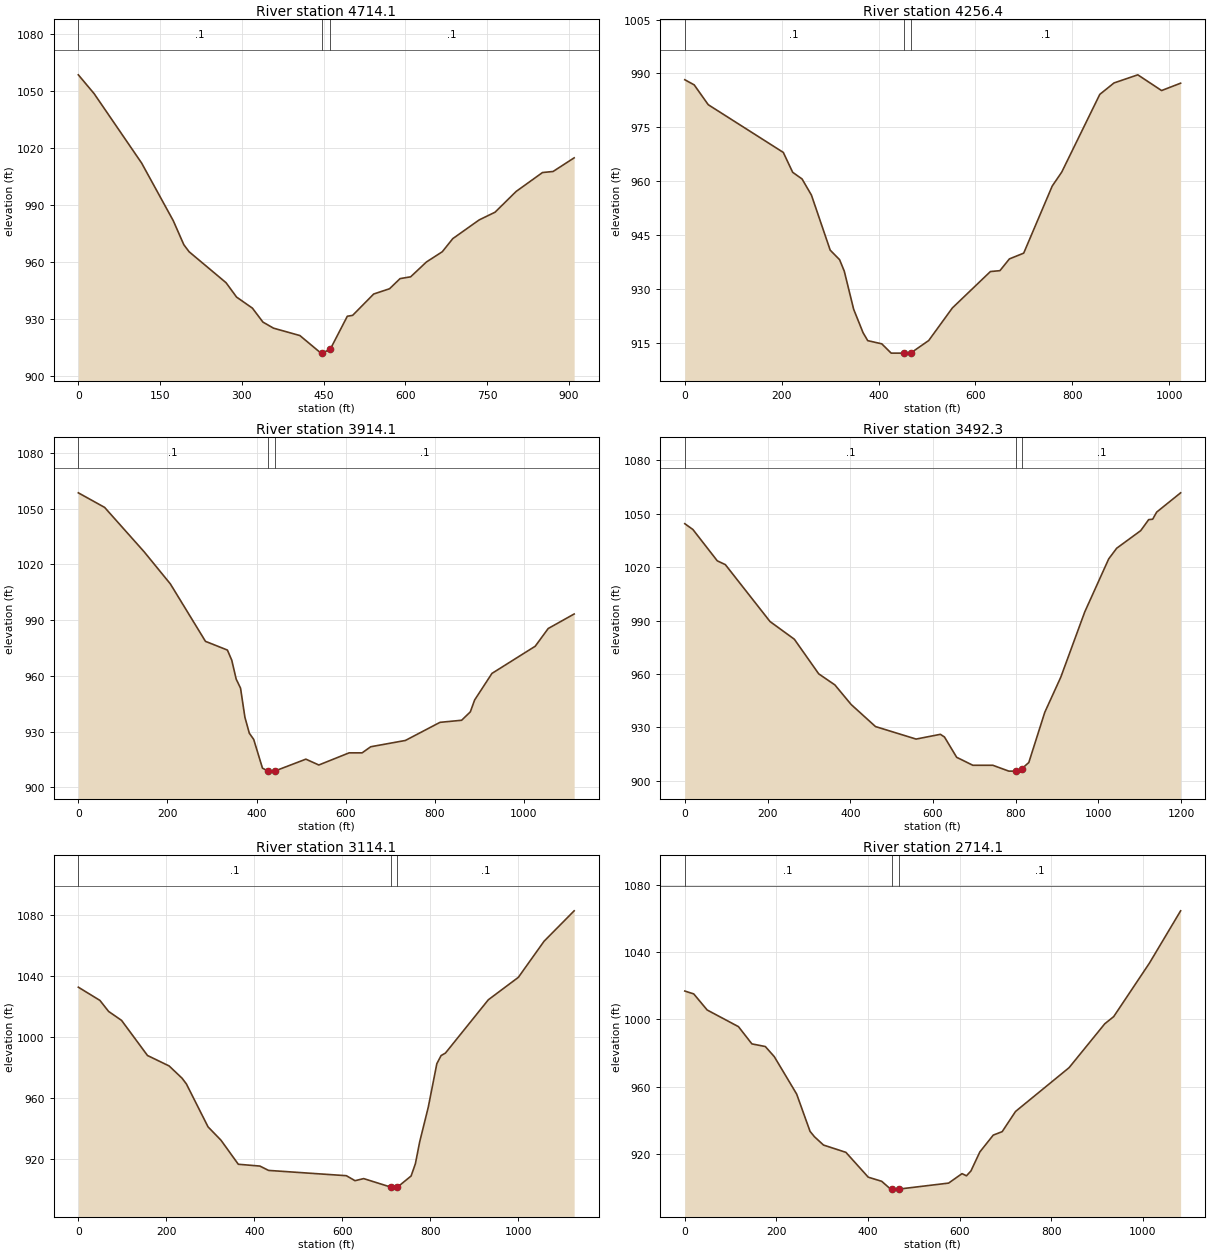
Type RM Length L Ch R = 1 ,4714.1  ,461.842,457.694,453.546
XS GIS Cut Line= 3
       1743343.6      343249.157     1743071.081      342884.796
     1742798.563      342520.435
#Sta/Elev= 30
       0 1058.39      29 1048.49   116.2 1011.99   174.3  981.66   193.6  969.09
   203.3  965.37   271.1   949.1   290.4  941.55   319.5  935.72   338.8  928.39
   358.2   925.2   406.6  921.31   445.3  912.07   447.5  912.07   462.5  914.18
   493.7  931.47   503.4  931.92   542.1  943.15   571.2  945.92   590.5  951.25
   609.9  952.19   638.9     960     668  965.38   687.3  972.28   735.7  982.11
   764.8  986.16   803.5  997.07   851.9 1007.02   871.3 1007.57     910 1014.74
#Mann= 3 , 0 , 0
       0      .1       0   447.5    .045       0   462.5      .1       0
Bank Sta=447.5,462.5
XS Rating Curve= 0 ,0
Exp/Cntr=0.3,0.1

Type RM Length L Ch R = 1 ,4256.4  ,353.996,342.306,326.237
XS GIS Cut Line= 3
     1743783.431      342949.492     1743405.643      342587.894
     1742909.947      342517.009
#Sta/Elev= 30
       0  988.23    19.4   986.8    48.4  981.28   203.4  967.98   222.7  962.45
   242.1  960.59   261.5  956.08   300.2  940.76   319.6   938.1   329.3  934.89
   348.6   924.3     368  917.78   377.7  915.55   406.7  914.66   426.1  912.07
   451.9  912.07   466.9  912.14   503.6  915.58   552.4  924.65     631   934.8
   650.6  935.04   670.2  938.32   699.7  939.92   758.6  958.62   778.2  962.49
   856.8  984.15   886.2  987.34   935.3   989.6   984.4  985.22  1023.7  987.27
#Mann= 3 , 0 , 0
       0      .1       0   451.9    .045       0   466.9      .1       0
Bank Sta=451.9,466.9
XS Rating Curve= 0 ,0
Exp/Cntr=0.3,0.1

Type RM Length L Ch R = 1 ,3914.1  ,422.374,421.853,423.846
XS GIS Cut Line= 3
     1744027.675      342457.241     1743601.029      342384.073
     1742921.453      342368.686
#Sta/Elev= 30
       0 1058.51      59 1050.67   147.6 1026.81   206.6 1009.48   285.3  978.61
   334.5  973.92   344.3  968.46   354.2   958.3     364  953.42   373.8  937.76
   383.7  929.18   393.5  925.87   413.2   910.4   425.4  908.86   432.9  908.79
   440.4  908.79   510.6  915.23   539.7  912.09   607.7  918.63   636.8  918.63
   656.2  921.91   733.9  925.29   811.6  935.04   860.1  936.15   879.6  940.67
   889.3  947.07   928.1  961.35  1025.2  975.97  1054.4  985.52  1112.6  993.32
#Mann= 3 , 0 , 0
       0      .1       0   425.4    .045       0   440.4      .1       0
Bank Sta=425.4,440.4
XS Rating Curve= 0 ,0
Exp/Cntr=0.3,0.1

Type RM Length L Ch R = 1 ,3492.3  ,370.103,378.147,405.292
XS GIS Cut Line= 3
     1744025.981       342403.29     1743402.412      342093.251
     1742903.828      342153.852
#Sta/Elev= 30
       0 1044.37    19.6 1041.12    78.5 1023.55    98.1 1021.39     206  989.47
   264.8  979.54   323.7  960.12   362.9  953.88   402.1  942.91     461  930.52
   559.1   923.5   617.9  926.17   627.7  924.67   657.2  913.27   696.4  908.79
   744.7  908.79   783.3  905.51     800  905.51     815  906.92   831.6  910.34
   870.2  938.52   908.9  958.23   966.8  994.84  1024.8 1024.65  1044.1 1030.62
  1102.1 1040.47  1121.4 1046.67    1131 1046.88  1140.7 1050.88  1198.6  1061.7
#Mann= 3 , 0 , 0
       0      .1       0     800    .045       0     815      .1       0
Bank Sta=800,815
XS Rating Curve= 0 ,0
Exp/Cntr=0.3,0.1

Type RM Length L Ch R = 1 ,3114.1  ,390.771,400,380.894
XS GIS Cut Line= 3
      1744075.41      342345.034     1743519.199      341892.037
     1743407.495      341497.903
#Sta/Elev= 30
       0 1032.77    49.1 1024.07    68.8 1016.83    98.3 1010.92   157.2  987.85
   206.4  980.96   235.8   972.9   245.7   969.1   294.8  940.92   324.3  932.12
   363.6  916.32   412.7  915.12   432.4  912.27   609.2  908.79   628.9  905.51
   648.6  906.88   709.8  901.33   717.3  899.96   724.8  901.15   756.4   908.6
   766.1  916.64   775.9  931.05   795.4  953.84   814.9  982.48   824.6  987.81
   834.4  989.42   931.9 1024.48  1000.2 1039.26  1058.7 1063.02    1127 1082.99
#Mann= 3 , 0 , 0
       0      .1       0   709.8    .045       0   724.8      .1       0
Bank Sta=709.8,724.8
XS Rating Curve= 0 ,0
Exp/Cntr=0.3,0.1

Type RM Length L Ch R = 1 ,2714.1  ,302.166,295.678,300.288
XS GIS Cut Line= 3
     1744145.991      342297.052     1743915.061      341900.225
     1743497.152      341437.675
#Sta/Elev= 30
       0 1016.86    19.5 1015.17    48.8  1005.6   117.2  995.66   146.5  985.41
   175.8  983.84   195.4  977.81   244.2  955.56   273.5  933.31   283.3  930.08
   302.8  925.19   351.7  920.85   400.5  906.07   429.8  903.62   449.4  898.95
   451.6  898.95   466.6  898.95     576  902.54   605.2  908.17     615  906.89
   624.7  909.77   644.2   921.1   673.4   931.1   692.9  933.16   722.1  945.19
     839  971.26   916.9  997.38   936.4 1001.65  1014.3 1033.45  1082.5 1064.62
#Mann= 3 , 0 , 0
       0      .1       0   451.6    .045       0   466.6      .1       0
Bank Sta=451.6,466.6
XS Rating Curve= 0 ,0
Exp/Cntr=0.3,0.1

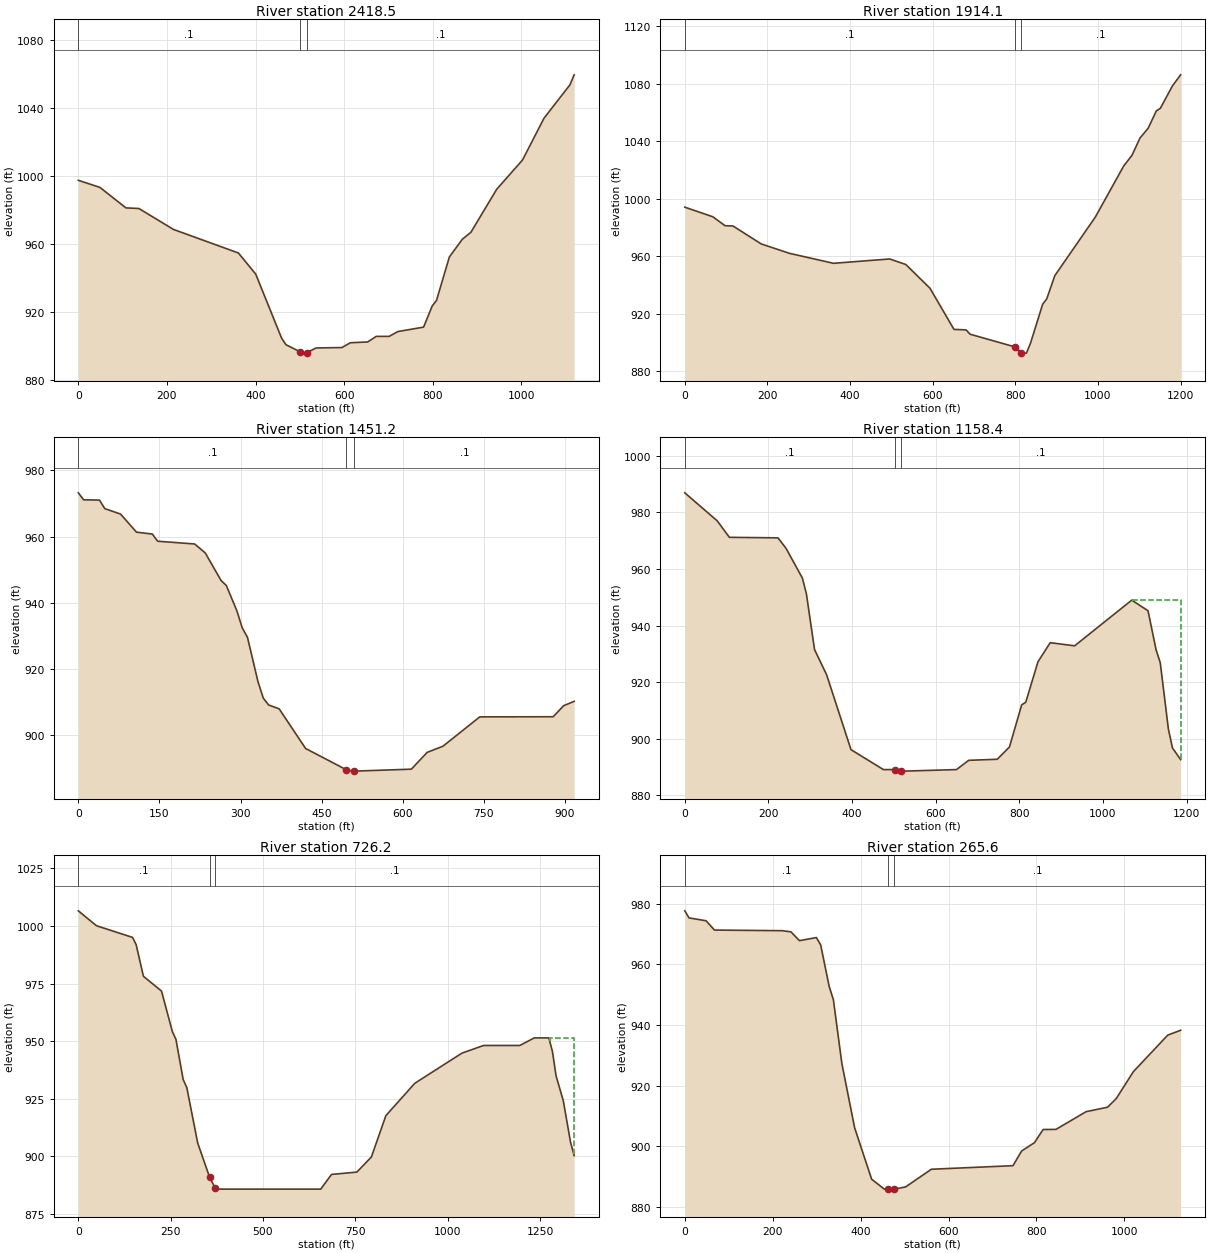
Type RM Length L Ch R = 1 ,2418.5  ,491.037,504.322,519.466
XS GIS Cut Line= 3
     1744373.649      342113.567     1744134.234       341756.76
     1743561.929      341372.345
#Sta/Elev= 30
       0  997.26    48.8  993.08   107.4  981.05   136.7  980.68   214.8  968.37
   361.3  954.53   400.4  942.11   458.8  904.46   468.5  900.64   500.4  896.46
   507.4  895.67   515.4  895.89   536.5   898.7   594.8  898.95   614.2  901.78
     653  902.23   672.4  905.51   701.6  905.51     721  908.34   779.3  910.96
   798.7  923.37   808.4  926.65   837.5  952.22   866.6  962.58   886.1  966.72
   944.3  991.99  1002.6 1009.21  1051.1 1033.78  1109.4 1053.31  1119.1 1059.26
#Mann= 3 , 0 , 0
       0      .1       0   500.4    .045       0   515.4      .1       0
Bank Sta=500.4,515.4
XS Rating Curve= 0 ,0
Exp/Cntr=0.3,0.1

Type RM Length L Ch R = 1 ,1914.1  ,453.068,462.93,465.842
XS GIS Cut Line= 3
     1744411.346      342080.614     1744116.884         341329.
      1744017.23      340949.009
#Sta/Elev= 30
       0  994.09    68.1  987.36    97.3  981.18   116.7  980.97   184.8   968.5
   252.9  961.96   359.9  954.98     496     958   534.9  954.15   593.3  937.66
   651.6  908.93   680.8   908.6   690.5  905.59   799.7  896.69   814.7  892.82
   817.1  892.41   826.9  892.43   836.7  899.27   866.2   926.5     876  930.16
   895.6  946.38   993.8  987.25  1062.6  1022.9  1082.2 1030.13  1101.9  1042.3
  1121.5 1049.04  1141.2  1061.1    1151 1062.94  1180.4  1078.6  1200.1 1086.27
#Mann= 3 , 0 , 0
       0      .1       0   799.7    .045       0   814.7      .1       0
Bank Sta=799.7,814.7
XS Rating Curve= 0 ,0
Exp/Cntr=0.3,0.1

Type RM Length L Ch R = 1 ,1451.2  ,280.57,292.851,305.244
XS GIS Cut Line= 3
     1744561.928      341928.681     1744494.615      341247.586
     1744555.198      341022.772
#Sta/Elev= 30
       0  973.24     9.8  971.13    39.1  971.05    48.9  968.47    78.2  966.81
   107.6  961.35   136.9  960.78   146.7  958.61   215.1  957.78   234.7   955.1
     264  946.75   273.8  945.21   293.3  937.57   303.1  932.46   312.9  929.54
   332.4  916.11   342.2  911.16     352  909.11   371.5  907.94   420.4  895.96
   495.7  889.53   508.4  889.11   510.7  889.11     616   889.7   645.3  894.78
   674.6  896.65   742.6  905.51   878.4  905.55   897.8  908.89   917.2  910.21
#Mann= 3 , 0 , 0
       0      .1       0   495.7    .045       0   510.7      .1       0
Bank Sta=495.7,510.7
XS Rating Curve= 0 ,0
Exp/Cntr=0.3,0.1

Type RM Length L Ch R = 1 ,1158.4  ,438.462,432.121,425.667
XS GIS Cut Line= 3
     1744600.809      342082.869     1744778.964       341508.96
      1744661.41      340936.233
#Sta/Elev= 30
       0  986.89    77.5     977   106.6  971.17   222.9  970.98   242.3  967.23
   281.1  956.79   290.8   951.2   310.2  931.53   339.2  922.58   397.4  896.16
   474.9  889.11   501.7  889.11   516.7  888.65   523.4  888.57   649.6  889.11
   678.9  892.39   747.1  892.76   776.3   897.1   805.6  911.99   815.3  912.91
   844.5  927.19   873.8  933.94   932.2  932.84  1068.7  948.98  1107.6  945.24
  1127.1  931.34  1136.9  926.88  1156.4  903.38  1166.1  896.76  1185.6  892.64
#Mann= 3 , 0 , 0
       0      .1       0   501.7    .045       0   516.7      .1       0
#XS Ineff= 2 , 0
                          1068.2          948.98
Permanent Ineff=
       F       F
Bank Sta=501.7,516.7
XS Rating Curve= 0 ,0
Exp/Cntr=0.3,0.1

Type RM Length L Ch R = 1 ,726.2   ,496.199,460.64,425.081
XS GIS Cut Line= 3
     1745062.937      342224.611     1745062.366      341754.694
       1744720.3      340951.968
#Sta/Elev= 30
       0 1006.57    48.9 1000.12   146.8  995.04   156.6  991.87   176.2  978.18
   225.2  971.76   254.5  954.25   264.3   950.8   283.9  933.35   293.7   929.9
   323.1  905.89   355.7  890.88   370.7  886.25   381.8  885.83   656.2  885.83
   685.6  892.21   754.2  893.22   793.5  899.78   832.7  917.71   911.1  931.76
  1038.6  944.82  1097.4  948.16  1195.4  948.16  1234.6  951.44  1273.9  951.44
  1283.7  945.57  1293.5  934.99  1313.1  924.17  1332.7  906.19  1342.5  900.37
#Mann= 3 , 0 , 0
       0      .1       0   355.7    .045       0   370.7      .1       0
#XS Ineff= 2 , 0
                            1276           951.6
Permanent Ineff=
       F       F
Bank Sta=355.7,370.7
XS Rating Curve= 0 ,0
Exp/Cntr=0.3,0.1

Type RM Length L Ch R = 1 ,265.6   ,268.389,265.596,262.804
XS GIS Cut Line= 3
     1745855.173      341625.549     1745352.942      341627.343
     1744972.681      341130.493
#Sta/Elev= 30
       0  977.69     9.7  975.35    48.3  974.41    67.6  971.34   222.1  971.13
   241.5  970.75   260.8  967.85   299.4  968.86   309.1  966.44   328.4  952.76
     338  948.35   357.4   927.2   386.3   906.1     425  889.11   453.9  885.83
   461.7  885.83   476.7  885.83   502.2  886.55   560.9  892.39   746.6  893.57
   766.2  898.41   795.5  901.18   815.1  905.51   844.4  905.55   912.8  911.39
   961.7  912.87   981.3  915.69  1020.4   924.6  1098.6  936.66  1127.9  938.27
#Mann= 3 , 0 , 0
       0      .1       0   461.7    .045       0   476.7      .1       0
Bank Sta=461.7,476.7
XS Rating Curve= 0 ,0
Exp/Cntr=0.3,0.1

Chan Stop Cuts=-1
Use User Specified Reach Order=0